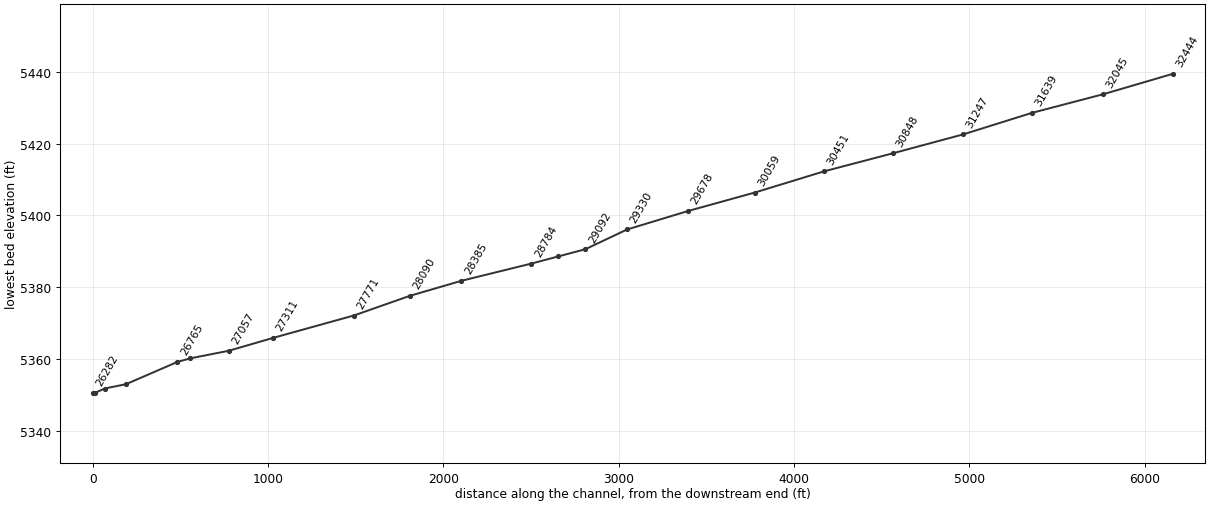
--- NBCalab.prj (project) ---

Proj Title=North Branch Calabacillas Arroyo
Current Plan=p08
Default Exp/Contr=0.3,0.1
English Units
Geom File=g03
Geom File=g04
Geom File=g06
Geom File=g05
Flow File=f07
Flow File=f06
Flow File=f05
Flow File=f04
Flow File=f03
Flow File=f02
Flow File=f01
Plan File=p08
Plan File=p03
Plan File=p06
Plan File=p05
Plan File=p01
Plan File=p02
Plan File=p04
Plan File=p07
Plan File=p09
Y Axis Title=Elevation
X Axis Title(PF)=Main Channel Distance
X Axis Title(XS)=Station
BEGIN DESCRIPTION:
North Branch Calabacillas Arroyo
    MUSSETTER ENGINEERING, INC.  APRIL, 1996
    MAIN BRANCH, CALABACILLAS ARROYO (U/S OF SWINBURNE DAM)
END DESCRIPTION:
DSS Export Rating Curves= 0
DSS Export Rating Curve Sorted= 0
DSS Export Volume Flow Curves= 0
DXF OffsetX= 0
DXF OffsetY= 0
DXF ScaleX= 1
DXF ScaleY= 10

--- NBCalab.p08 (plan) ---

Plan Title=Design Cond at Exist Grd, Peak Qs BULKED
Program Version=3.12
Short Identifier=DesExGPksBLK
Geom File=g03
Flow File=f07
Subcritical Flow
K Sum by GR= 0
Std Step Tol= 0.01
Critical Tol= 0.01
Num of Std Step Trials= 20
Max Error Tol= 0.3
Flow Tol Ratio= 0.001
Split Flow NTrial= 30
Split Flow Tol= 0.02
Split Flow Ratio= 0.02
Log Output Level= 0
Friction Slope Method= 1
Unsteady Friction Slope Method= 2
Unsteady Bridges Friction Slope Method= 1
Parabolic Critical Depth
Global Vel Dist= 0 , 0 , 0
Global Log Level= 0
CheckData=True
Encroach Param=-1 ,0,0, 0
BEGIN DESCRIPTION:
North Branch Calabacillas Arroyo, Peak Qs (Future, BULKED)
Design Conditions (NGVD29)
at Existing Grade
END DESCRIPTION:
Computation Interval=1HOUR
Output Interval=1HOUR
Run HTab= 0
Run UNet= 0
Run PostProcess= 0
UNET Theta= 1
UNET Theta Warmup= 1
UNET ZTol= 0.02
UNET ZSATol= 0.05
UNET MxIter= 20
UNET MaxInSteps= 0
UNET DtIC= 0
UNET DtMin= 0
UNET MaxCRTS= 20
UNET WFStab= 2
UNET SFStab= 1
UNET WFX= 1
UNET SFX= 1
UNET DSS MLevel= 4
UNET DZMax Abort= 100
UNET Convert EG Bridges=-1
UNET Use Existing IB Tables=-1
UNET Froude Reduction=False
UNET Froude Limit= 1
UNET Froude Power= 10
Instantaneous Interval=1HOUR
Write IC File= 0
Echo Input=False
Echo Output=False
Write Detailed= 0
Detailed Automatic Start=False, 10

--- NBCalab.p01 (plan) ---

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Plan Title=NB Calabacillas, Existing Cond, Rng of Q
Short Identifier=NBCalabEXRng
Geom File=g06
Flow File=f04
North Branch Calabacillas Arroyo, Range of Qs (Future)
Existing Conditions (NGVD29)
Using most recent mapping (2003 or 2000)

--- NBCalab.p02 (plan) ---

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Plan Title=NB Calabacillas, Existing Cond Pk Qs
Short Identifier=NBCalabEXpk
Geom File=g06
Flow File=f03
North Branch Calabacillas Arroyo, Peak Qs (Future)
Existing Conditions (NGVD29)
Using most-recent mapping (2003 or 2000)

--- NBCalab.p03 (plan) ---

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Plan Title=Design Cond at Eq Slope, Peak Qs
Short Identifier=DesignEqSPks
Geom File=g04
Flow File=f06
North Branch Calabacillas Arroyo, Peak Qs (Future)
at Equilibrium Slope

--- NBCalab.p04 (plan) ---

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Plan Title=Design Cond at Exist Grade, Rng of Qs
Short Identifier=DesignExGRng
Geom File=g03
Flow File=f05
North Branch Calabacillas Arroyo, Range of Qs (Future)
at Present (Existing) Grade

--- NBCalab.p05 (plan) ---

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Plan Title=Design Cond at Exist Grade, Peak Qs
Short Identifier=DesignExGPks
Geom File=g03
Flow File=f06
North Branch Calabacillas Arroyo, Peak Qs (Future)

--- NBCalab.p06 (plan) ---

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Plan Title=Design Cond at Eq Slope, Rng of Qs
Short Identifier=DesCondEqSR
Geom File=g04
Flow File=f05
North Branch Calabacillas Arroyo, Range of Qs (Future)
at Equilibrium Slope

--- NBCalab.p07 (plan) ---

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Plan Title=Design Cond at Eq Slope, Peak Qs BULKED
Short Identifier=DesEQSpksBLK
Geom File=g04
Flow File=f07
at Equilibrium Slope

--- NBCalab.p09 (plan) ---

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Plan Title=Design Cond at Ex Grd, Peak Qs BULK-RedN
Short Identifier=DesExGrdPksN
Geom File=g05
Flow File=f07
at Existing Grade, with Reduced n values in US reach

--- NBCalab.f07 (steady flow) ---

Flow Title=Design Cond, Peak Flows, BULKED
Program Version=3.12
Number of Profiles= 7
Profile Names=2-yr,5-yr,10-yr,25-yr,50-yr,100-yr,500-yr
River Rch & RM=Calabacillas,N Branch        ,32444
    2054    3675    5099    6811    8276    9786   13401
River Rch & RM=Calabacillas,N Branch        ,30059
    2967    5184    7148    9513   11523   13599   18268
River Rch & RM=Calabacillas,N Branch        ,25000
    3277    5681    7809   10352   12508   14734   19611
River Rch & RM=Calabacillas,N Branch        ,21945.
    3895    6636    9058   11945   14364   16842   23133
Boundary for River Rch & Prof#=Calabacillas,N Branch        , 1
Up Type= 0
Dn Type= 4
Dn Rating Curve # Pts= 12
       0  5259.2     400    5260    1500    5265    2200    5267    3000    5270
    4900    5275    7990    5280   12800    5285   16200    5288   19900    5290
   46200    5295   68000    5298
Boundary for River Rch & Prof#=Calabacillas,N Branch        , 2
Up Type= 0
Dn Type= 0
Boundary for River Rch & Prof#=Calabacillas,N Branch        , 3
Up Type= 0
Dn Type= 0
Boundary for River Rch & Prof#=Calabacillas,N Branch        , 4
Up Type= 0
Dn Type= 0
Boundary for River Rch & Prof#=Calabacillas,N Branch        , 5
Up Type= 0
Dn Type= 0
Boundary for River Rch & Prof#=Calabacillas,N Branch        , 6
Up Type= 0
Dn Type= 0
DSS Import GetInterval= 0
DSS Import GetPeak= 0
DSS Import FillOption= 0

--- NBCalab.f01 (steady flow) ---

Flow Title=NB Calabacillas, Range of Flows
Program Version=3.12
Number of Profiles= 9
Profile Names=PF 1,PF 2,PF 3,PF 4,PF 5,PF 6,PF 7,PF 8,PF 9
River Rch & RM=Calabacillas,N Branch        ,32526.
      57     114     285     570    1140    2850    5710    7420    9700
River Rch & RM=Calabacillas,N Branch        ,30137.
      78     156     390     780    1560    3900    7800   10140   13260
River Rch & RM=Calabacillas,N Branch        ,25385.
      85     169     423     845    1690    4225    8450   10985   14365
River Rch & RM=Calabacillas,N Branch        ,21945.
     100     200     500    1000    2000    5000   10000   13000   17000
River Rch & RM=Calabacillas,N Branch        ,19845.
     100     200     500    1000    2000    5000   10000   13000   17000
Boundary for River Rch & Prof#=Calabacillas,N Branch        , 1
Up Type= 0
Dn Type= 4
Dn Rating Curve # Pts= 12
       0    5262     400  5262.8    1500  5267.8    2200  5269.8    3000  5272.8
    4900  5277.8    7990  5282.8   12800  5287.8   16200  5290.8   19900  5292.8
   46200  5297.8   68000  5300.8
Boundary for River Rch & Prof#=Calabacillas,N Branch        , 2
Up Type= 0
Dn Type= 0
Boundary for River Rch & Prof#=Calabacillas,N Branch        , 3
Up Type= 0
Dn Type= 0
Boundary for River Rch & Prof#=Calabacillas,N Branch        , 4
Up Type= 0
Dn Type= 0
Boundary for River Rch & Prof#=Calabacillas,N Branch        , 5
Up Type= 0
Dn Type= 0
Boundary for River Rch & Prof#=Calabacillas,N Branch        , 6
Up Type= 0
Dn Type= 0
Boundary for River Rch & Prof#=Calabacillas,N Branch        , 7
Up Type= 0
Dn Type= 0
Boundary for River Rch & Prof#=Calabacillas,N Branch        , 8
Up Type= 0
Dn Type= 0
Boundary for River Rch & Prof#=Calabacillas,N Branch        , 9
Up Type= 0
Dn Type= 0
DSS Import GetInterval= 0
DSS Import GetPeak= 0
DSS Import FillOption= 0

--- NBCalab.f02 (steady flow) ---

Flow Title=NB Calabacillas, Peak Flows
Program Version=3.12
Number of Profiles= 6
Profile Names=2-yr,5-yr,10-yr,25-yr,50-yr,100-yr
River Rch & RM=Calabacillas,N Branch        ,32526.
    2003    3570    4953    6627    8063    9538
River Rch & RM=Calabacillas,N Branch        ,30137.
    2890    5031    6927    9200   11124   13107
River Rch & RM=Calabacillas,N Branch        ,25385.
    3173    5478    7527    9968   12025   14136
River Rch & RM=Calabacillas,N Branch        ,21945.
    3876    6605    9016   11890   14298   16764
Boundary for River Rch & Prof#=Calabacillas,N Branch        , 1
Up Type= 0
Dn Type= 4
Dn Rating Curve # Pts= 12
       0    5262     400  5262.8    1500  5267.8    2200  5269.8    3000  5272.8
    4900  5277.8    7990  5282.8   12800  5287.8   16200  5290.8   19900  5292.8
   46200  5297.8   68000  5300.8
Boundary for River Rch & Prof#=Calabacillas,N Branch        , 2
Up Type= 0
Dn Type= 0
Boundary for River Rch & Prof#=Calabacillas,N Branch        , 3
Up Type= 0
Dn Type= 0
Boundary for River Rch & Prof#=Calabacillas,N Branch        , 4
Up Type= 0
Dn Type= 0
Boundary for River Rch & Prof#=Calabacillas,N Branch        , 5
Up Type= 0
Dn Type= 0
Boundary for River Rch & Prof#=Calabacillas,N Branch        , 6
Up Type= 0
Dn Type= 0
DSS Import GetInterval= 0
DSS Import GetPeak= 0
DSS Import FillOption= 0

--- NBCalab.f03 (steady flow) ---

Flow Title=NB Calabacillas, Peak Flows, NGVD29
Program Version=3.12
Number of Profiles= 6
Profile Names=2-yr,5-yr,10-yr,25-yr,50-yr,100-yr
River Rch & RM=Calabacillas,N Branch        ,32526.
    2003    3570    4953    6627    8063    9538
River Rch & RM=Calabacillas,N Branch        ,30137.
    2890    5031    6927    9200   11124   13107
River Rch & RM=Calabacillas,N Branch        ,25385.
    3173    5478    7527    9968   12025   14136
River Rch & RM=Calabacillas,N Branch        ,21945.
    3876    6605    9016   11890   14298   16764
Boundary for River Rch & Prof#=Calabacillas,N Branch        , 1
Up Type= 0
Dn Type= 4
Dn Rating Curve # Pts= 12
       0  5259.2     400    5260    1500    5265    2200    5267    3000    5270
    4900    5275    7990    5280   12800    5285   16200    5288   19900    5290
   46200    5295   68000    5298
Boundary for River Rch & Prof#=Calabacillas,N Branch        , 2
Up Type= 0
Dn Type= 0
Boundary for River Rch & Prof#=Calabacillas,N Branch        , 3
Up Type= 0
Dn Type= 0
Boundary for River Rch & Prof#=Calabacillas,N Branch        , 4
Up Type= 0
Dn Type= 0
Boundary for River Rch & Prof#=Calabacillas,N Branch        , 5
Up Type= 0
Dn Type= 0
Boundary for River Rch & Prof#=Calabacillas,N Branch        , 6
Up Type= 0
Dn Type= 0
DSS Import GetInterval= 0
DSS Import GetPeak= 0
DSS Import FillOption= 0

--- NBCalab.f04 (steady flow) ---

Flow Title=NB Calabacillas, Range of Flows, NGVD29
Program Version=3.12
Number of Profiles= 9
Profile Names=PF 1,PF 2,PF 3,PF 4,PF 5,PF 6,PF 7,PF 8,PF 9
River Rch & RM=Calabacillas,N Branch        ,32526.
      57     114     285     570    1140    2850    5710    7420    9700
River Rch & RM=Calabacillas,N Branch        ,30137.
      78     156     390     780    1560    3900    7800   10140   13260
River Rch & RM=Calabacillas,N Branch        ,25385.
      85     169     423     845    1690    4225    8450   10985   14365
River Rch & RM=Calabacillas,N Branch        ,21945.
     100     200     500    1000    2000    5000   10000   13000   17000
River Rch & RM=Calabacillas,N Branch        ,19845.
     100     200     500    1000    2000    5000   10000   13000   17000
Boundary for River Rch & Prof#=Calabacillas,N Branch        , 1
Up Type= 0
Dn Type= 4
Dn Rating Curve # Pts= 12
       0  5259.2     400    5260    1500    5265    2200    5267    3000    5270
    4900    5275    7990    5280   12800    5285   16200    5288   19900    5290
   46200    5295   68000    5298
Boundary for River Rch & Prof#=Calabacillas,N Branch        , 2
Up Type= 0
Dn Type= 0
Boundary for River Rch & Prof#=Calabacillas,N Branch        , 3
Up Type= 0
Dn Type= 0
Boundary for River Rch & Prof#=Calabacillas,N Branch        , 4
Up Type= 0
Dn Type= 0
Boundary for River Rch & Prof#=Calabacillas,N Branch        , 5
Up Type= 0
Dn Type= 0
Boundary for River Rch & Prof#=Calabacillas,N Branch        , 6
Up Type= 0
Dn Type= 0
Boundary for River Rch & Prof#=Calabacillas,N Branch        , 7
Up Type= 0
Dn Type= 0
Boundary for River Rch & Prof#=Calabacillas,N Branch        , 8
Up Type= 0
Dn Type= 0
Boundary for River Rch & Prof#=Calabacillas,N Branch        , 9
Up Type= 0
Dn Type= 0
DSS Import GetInterval= 0
DSS Import GetPeak= 0
DSS Import FillOption= 0

--- NBCalab.f05 (steady flow) ---

Flow Title=Design Cond, Range of Flows, NGVD29
Program Version=3.12
Number of Profiles= 9
Profile Names=PF 1,PF 2,PF 3,PF 4,PF 5,PF 6,PF 7,PF 8,PF 9
River Rch & RM=Calabacillas,N Branch        ,32444
      57     114     285     570    1140    2850    5710    7420    9700
River Rch & RM=Calabacillas,N Branch        ,30059
      78     156     390     780    1560    3900    7800   10140   13260
River Rch & RM=Calabacillas,N Branch        ,25660
      85     169     423     845    1690    4225    8450   10985   14365
River Rch & RM=Calabacillas,N Branch        ,21945.
     100     200     500    1000    2000    5000   10000   13000   17000
River Rch & RM=Calabacillas,N Branch        ,19845.
     100     200     500    1000    2000    5000   10000   13000   17000
Boundary for River Rch & Prof#=Calabacillas,N Branch        , 1
Up Type= 0
Dn Type= 4
Dn Rating Curve # Pts= 12
       0  5259.2     400    5260    1500    5265    2200    5267    3000    5270
    4900    5275    7990    5280   12800    5285   16200    5288   19900    5290
   46200    5295   68000    5298
Boundary for River Rch & Prof#=Calabacillas,N Branch        , 2
Up Type= 0
Dn Type= 0
Boundary for River Rch & Prof#=Calabacillas,N Branch        , 3
Up Type= 0
Dn Type= 0
Boundary for River Rch & Prof#=Calabacillas,N Branch        , 4
Up Type= 0
Dn Type= 0
Boundary for River Rch & Prof#=Calabacillas,N Branch        , 5
Up Type= 0
Dn Type= 0
Boundary for River Rch & Prof#=Calabacillas,N Branch        , 6
Up Type= 0
Dn Type= 0
Boundary for River Rch & Prof#=Calabacillas,N Branch        , 7
Up Type= 0
Dn Type= 0
Boundary for River Rch & Prof#=Calabacillas,N Branch        , 8
Up Type= 0
Dn Type= 0
Boundary for River Rch & Prof#=Calabacillas,N Branch        , 9
Up Type= 0
Dn Type= 0
DSS Import GetInterval= 0
DSS Import GetPeak= 0
DSS Import FillOption= 0

--- NBCalab.f06 (steady flow) ---

Flow Title=Design Cond, Peak Flows, NGVD29
Program Version=3.12
Number of Profiles= 7
Profile Names=2-yr,5-yr,10-yr,25-yr,50-yr,100-yr,500-yr
River Rch & RM=Calabacillas,N Branch        ,32444
    2003    3570    4953    6627    8063    9538   13401
River Rch & RM=Calabacillas,N Branch        ,30059
    2890    5031    6927    9200   11124   13107   18268
River Rch & RM=Calabacillas,N Branch        ,25000
    3173    5478    7527    9968   12025   14136   19611
River Rch & RM=Calabacillas,N Branch        ,21945.
    3876    6605    9016   11890   14298   16764   23133
Boundary for River Rch & Prof#=Calabacillas,N Branch        , 1
Up Type= 0
Dn Type= 4
Dn Rating Curve # Pts= 12
       0  5259.2     400    5260    1500    5265    2200    5267    3000    5270
    4900    5275    7990    5280   12800    5285   16200    5288   19900    5290
   46200    5295   68000    5298
Boundary for River Rch & Prof#=Calabacillas,N Branch        , 2
Up Type= 0
Dn Type= 0
Boundary for River Rch & Prof#=Calabacillas,N Branch        , 3
Up Type= 0
Dn Type= 0
Boundary for River Rch & Prof#=Calabacillas,N Branch        , 4
Up Type= 0
Dn Type= 0
Boundary for River Rch & Prof#=Calabacillas,N Branch        , 5
Up Type= 0
Dn Type= 0
Boundary for River Rch & Prof#=Calabacillas,N Branch        , 6
Up Type= 0
Dn Type= 0
DSS Import GetInterval= 0
DSS Import GetPeak= 0
DSS Import FillOption= 0

--- NBCalab.g03 (geometry) ---

Geom Title=Revised Design Cond at Exist Grade, VD29
Program Version=3.12

River Reach=Calabacillas    ,N Branch
Reach XY= 2
              .5             .95              .5             .05

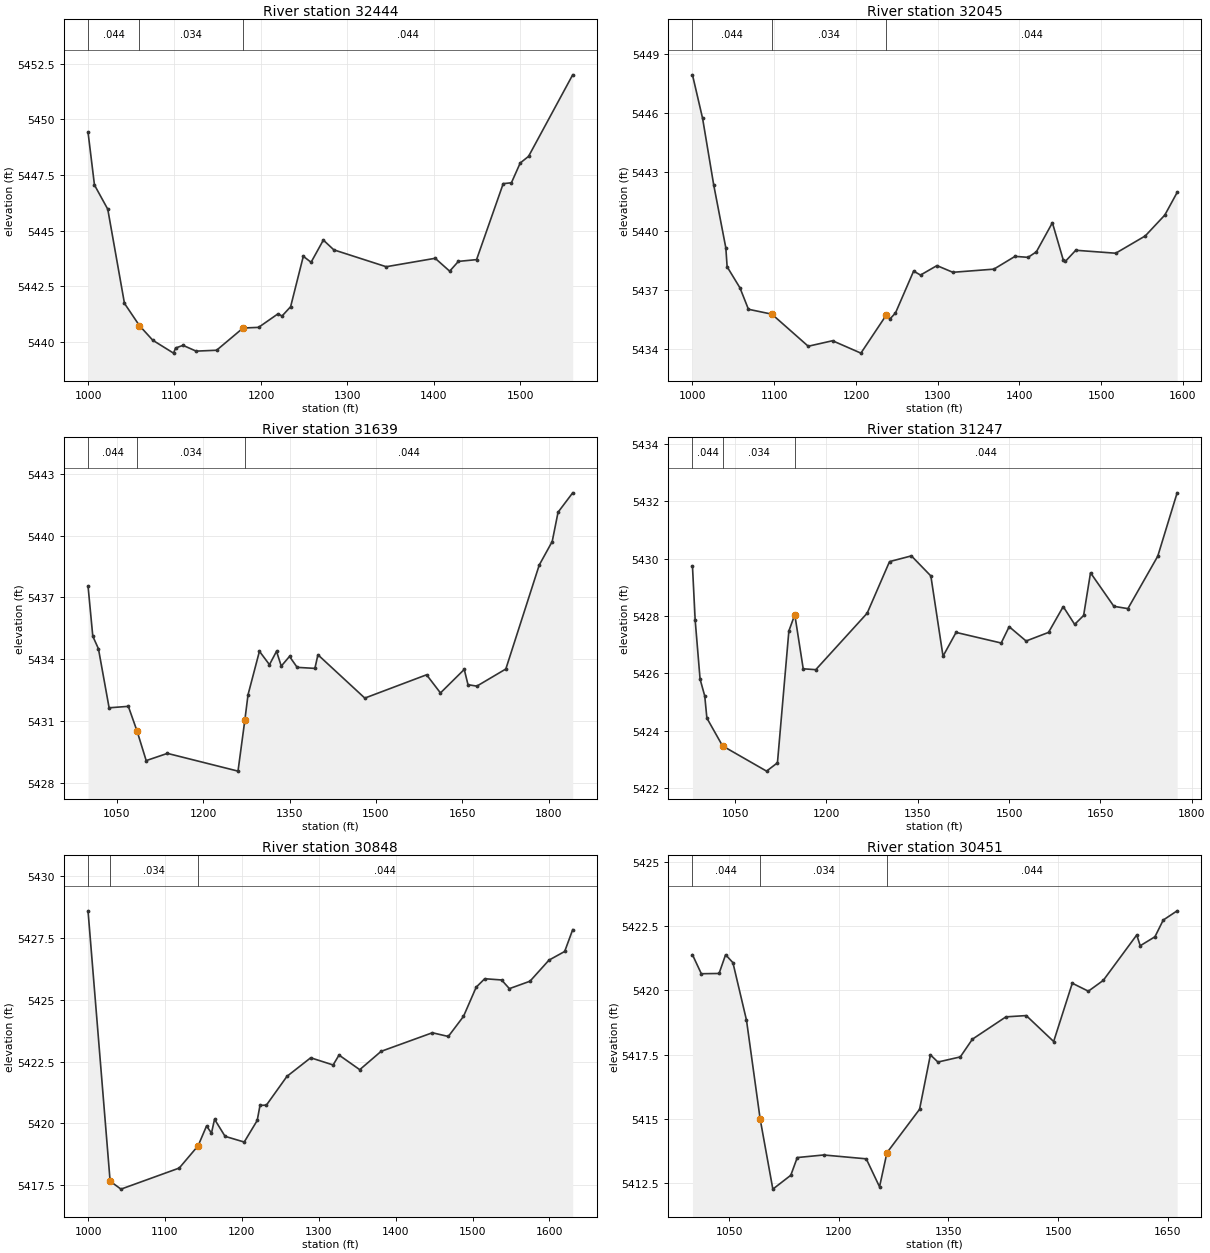
Type RM Length L Ch R = 1 ,32444   ,400,399,380
#Sta/Elev= 30
    1000 5449.43 1007.45 5447.05 1022.83 5445.96 1042.15 5441.72 1059.44 5440.72
  1074.9 5440.06 1098.88 5439.48 1101.28 5439.71 1109.89 5439.83 1125.02 5439.57
 1148.71 5439.61  1179.3 5440.61 1197.24 5440.64 1219.74 5441.25 1224.36 5441.15
 1234.31 5441.57 1248.99 5443.84 1257.98 5443.57 1272.16 5444.57 1284.27 5444.13
 1344.85 5443.37 1401.51 5443.75 1418.27 5443.17 1428.33 5443.61 1449.37 5443.69
 1480.18 5447.11 1489.67 5447.15 1499.85 5448.04 1509.51 5448.34 1560.54 5452.01
#Mann= 3 , 0 , 0
    1000    .044       0 1059.44    .034       0  1179.3    .044       0
Bank Sta=1059.44,1179.3
Sediment Elevation=0
Exp/Cntr=0.3,0.1

Type RM Length L Ch R = 1 ,32045   ,410,406,380
#Sta/Elev= 30
    1000 5447.92 1012.37 5445.71 1025.96 5442.33 1040.82 5439.12  1042.4 5438.16
 1058.09 5437.09 1068.47    5436 1097.18 5435.75 1141.62 5434.12 1171.35  5434.4
 1206.06 5433.77 1237.19 5435.71 1241.39  5435.5 1248.34 5435.81 1270.55 5437.94
 1278.99 5437.74 1299.09 5438.22 1318.55 5437.88 1368.71 5438.04 1394.61 5438.69
 1410.55 5438.64  1420.7 5438.92 1440.32  5440.4 1453.79 5438.48 1456.06 5438.43
  1468.9    5439 1517.81 5438.85 1553.95 5439.73 1577.84 5440.79 1592.92 5441.94
#Mann= 3 , 0 , 0
    1000    .044       0 1097.18    .034       0 1237.19    .044       0
Bank Sta=1097.18,1237.19
Sediment Elevation=0
Exp/Cntr=0.3,0.1

Type RM Length L Ch R = 1 ,31639   ,390,392,410
#Sta/Elev= 30
    1000 5437.56 1008.28 5435.12 1018.11 5434.51 1036.62 5431.65 1070.03 5431.72
 1085.31 5430.51 1101.04 5429.09  1137.9 5429.44 1260.53 5428.58 1272.39 5431.05
 1277.92 5432.28 1297.75 5434.39 1315.17 5433.74 1327.43 5434.39 1335.67 5433.67
 1349.99 5434.14 1363.28 5433.61 1394.07 5433.56 1399.37 5434.22 1480.79 5432.12
 1588.09 5433.25 1612.18 5432.37 1653.53 5433.51 1660.04 5432.77 1675.39  5432.7
 1725.73 5433.53 1783.78 5438.57 1806.31 5439.71 1816.47 5441.13 1841.89 5442.07
#Mann= 3 , 0 , 0
    1000    .044       0 1085.31    .034       0 1272.39    .044       0
Bank Sta=1085.31,1272.39
Sediment Elevation=0
Exp/Cntr=0.3,0.1

Type RM Length L Ch R = 1 ,31247   ,420,399,330
#Sta/Elev= 30
     980 5429.74  984.44 5427.86   992.5  5425.8 1000.18 5425.21 1003.68 5424.44
 1029.44 5423.47 1101.73 5422.59  1119.6 5422.88 1138.36 5427.48 1148.09 5428.05
 1161.93 5426.16 1182.55 5426.13 1266.97  5428.1  1303.7  5429.9 1339.62  5430.1
  1371.6  5429.4 1391.58  5426.6 1412.99 5427.43 1487.15 5427.06 1500.22 5427.63
 1528.04 5427.13  1564.9 5427.43 1589.02 5428.33 1607.83 5427.71 1622.54 5428.02
 1633.87 5429.51 1672.25 5428.34  1695.3 5428.26 1744.34 5430.09 1776.16  5432.3
#Mann= 3 , 0 , 0
     980    .044       0 1029.44    .034       0 1148.09    .044       0
#Block Obstruct= 2 , 0
                         1654.63
Bank Sta=1029.44,1148.09
Sediment Elevation=0
Exp/Cntr=0.3,0.1

Type RM Length L Ch R = 1 ,30848   ,400,397,400
#Sta/Elev= 30
    1000 5428.58 1028.73 5417.67 1042.85 5417.35 1118.59  5418.2 1143.16  5419.1
 1154.14  5419.9 1160.52 5419.61 1164.52 5420.17 1178.22 5419.48  1203.1 5419.25
 1219.99 5420.12 1223.64 5420.73 1231.97 5420.74 1258.66  5421.9 1289.55 5422.65
 1318.71 5422.36 1326.38 5422.76 1353.32 5422.17 1381.11 5422.91 1447.77 5423.66
  1468.5 5423.51 1488.22 5424.32 1504.76  5425.5 1515.86 5425.84 1537.76 5425.79
 1547.93 5425.44  1574.7 5425.74 1599.36 5426.59 1619.81 5426.94 1630.23 5427.82
#Mann= 3 , 0 , 0
    1000    .044       0 1028.73    .034       0 1143.16    .044       0
Bank Sta=1028.73,1143.16
Sediment Elevation=0
Exp/Cntr=0.3,0.1

Type RM Length L Ch R = 1 ,30451   ,380,392,450
#Sta/Elev= 30
    1000 5421.39 1012.11 5420.65 1036.37 5420.66  1045.3 5421.39 1055.32 5421.08
 1073.88 5418.84 1092.56 5414.99 1109.91 5412.26 1134.45  5412.8 1143.29 5413.49
 1179.43 5413.59 1237.64 5413.44  1255.8 5412.35 1265.95 5413.68 1310.53 5415.37
 1325.35 5417.49 1335.62 5417.21 1366.23 5417.41 1382.75  5418.1 1428.63 5418.97
 1456.38 5419.02 1493.88 5418.01 1519.37 5420.28 1541.31 5419.97 1561.69 5420.39
  1607.5 5422.16 1612.25 5421.74 1632.38 5422.09  1643.7 5422.74 1662.72  5423.1
#Mann= 3 , 0 , 0
    1000    .044       0 1092.56    .034       0 1265.95    .044       0
Bank Sta=1092.56,1265.95
Sediment Elevation=0
Exp/Cntr=0.3,0.1

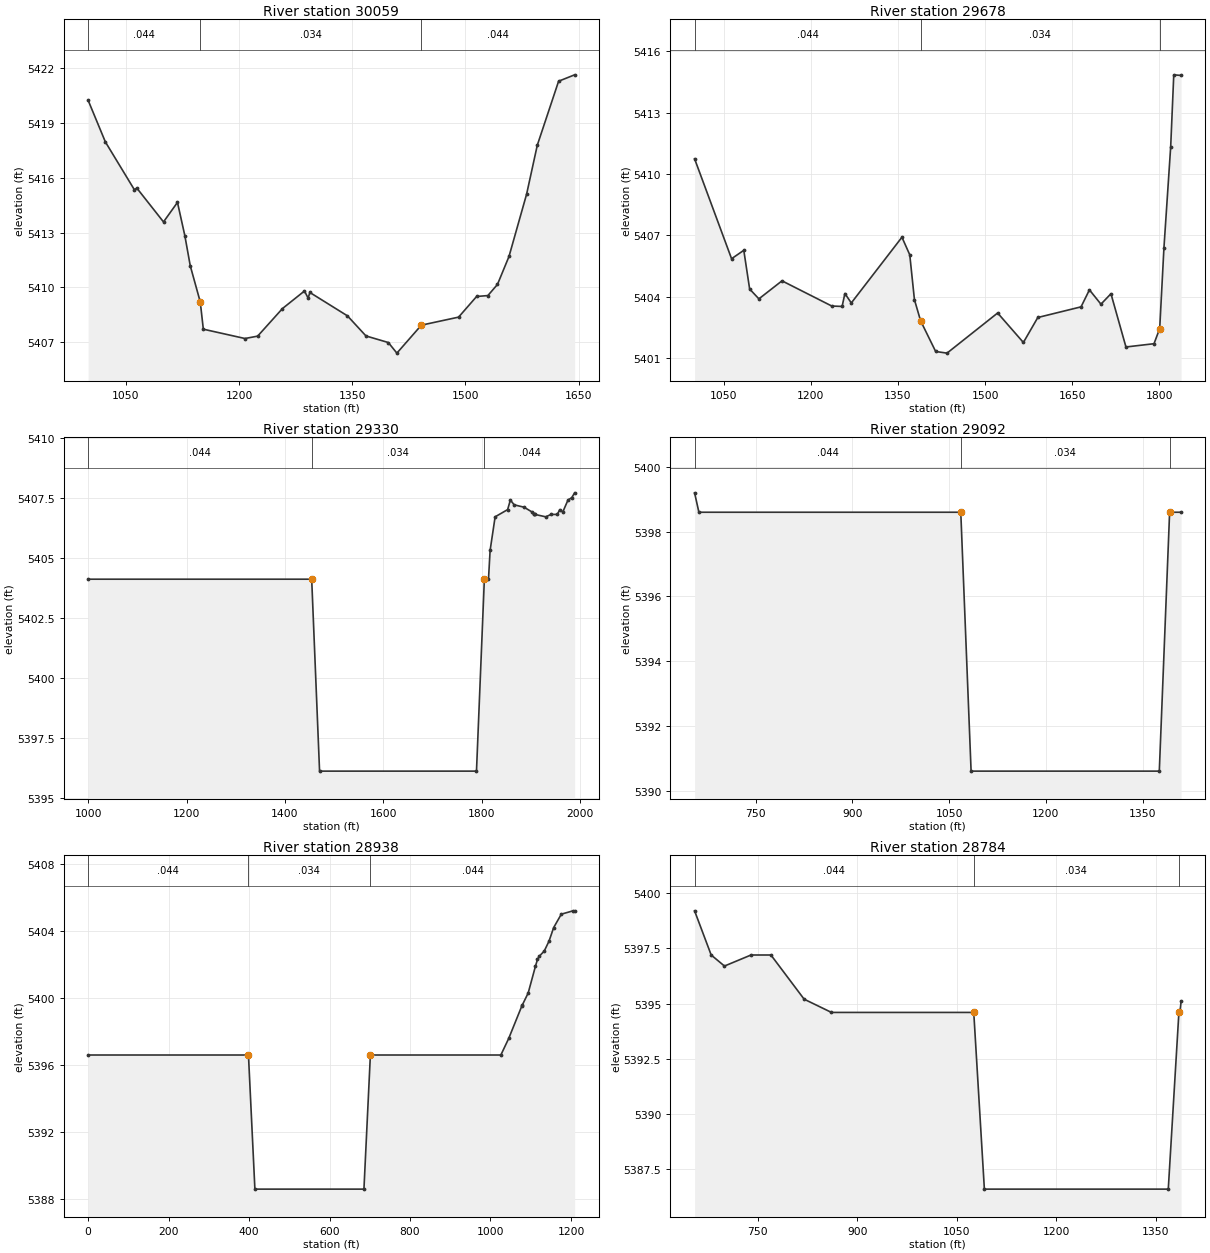
Type RM Length L Ch R = 1 ,30059   ,400,381,350
#Sta/Elev= 30
    1000 5420.24 1022.85 5417.96  1061.2 5415.35  1064.6 5415.43 1099.92 5413.58
 1118.43 5414.65 1128.19 5412.83 1135.38 5411.18 1148.64  5409.2  1152.7 5407.71
 1207.88  5407.2  1224.7 5407.33 1257.61 5408.84 1286.74  5409.8 1291.61 5409.41
 1293.89 5409.72 1343.71 5408.44 1368.28 5407.34  1397.9 5406.98 1409.24  5406.4
 1441.66 5407.93 1491.02 5408.37 1514.91  5409.5 1529.85 5409.55 1542.56 5410.16
 1557.83 5411.69 1581.17  5415.1 1595.35 5417.78 1623.57 5421.28 1644.81 5421.63
#Mann= 3 , 0 , 0
    1000    .044       0 1148.64    .034       0 1441.66    .044       0
Bank Sta=1148.64,1441.66
Sediment Elevation=0
Exp/Cntr=0.3,0.1

Type RM Length L Ch R = 1 ,29678   ,289,348,311
BEGIN DESCRIPTION:
Existing Section
END DESCRIPTION:
#Sta/Elev= 30
    1000 5410.74 1063.65 5405.86  1084.7 5406.27 1094.76 5404.38 1110.69  5403.9
 1150.45 5404.78  1236.1 5403.55  1253.9 5403.53 1258.69 5404.16 1269.72  5403.7
 1356.88 5406.91 1370.34 5406.05 1378.38 5403.86 1388.96 5402.83 1414.91 5401.33
 1434.47 5401.25 1521.58 5403.21 1565.88 5401.77 1590.71 5402.99 1665.14 5403.51
 1679.54 5404.34 1699.36 5403.64  1716.6 5404.15  1742.4 5401.55  1790.7 5401.71
  1800.5 5402.45  1807.8  5406.4  1819.4 5411.33  1824.7 5414.84  1837.3 5414.81
#Mann= 3 , 0 , 0
    1000    .044       0 1388.96    .034       0  1800.5    .044       0
#Block Obstruct= 2 , 0
         1357.19
Bank Sta=1388.96,1800.5
Sediment Elevation=0
Exp/Cntr=0.3,0.1

Type RM Length L Ch R = 1 ,29330   ,238,238,238
BEGIN DESCRIPTION:
Spur 10L
END DESCRIPTION:
#Sta/Elev= 24
    1000  5404.1  1454.5  5404.1  1470.5  5396.1  1789.5  5396.1  1805.5  5404.1
  1813.9  5404.1  1817.2  5405.3  1827.4  5406.7  1852.8    5407  1858.4  5407.4
  1866.1  5407.2  1886.3  5407.1  1902.5  5406.9  1906.9  5406.8  1907.2  5406.8
  1908.3  5406.8  1930.3  5406.7  1941.1  5406.8  1953.8  5406.8  1958.8    5407
  1964.9  5406.9  1975.5  5407.4  1983.2  5407.5    1989  5407.7
#Mann= 3 , 0 , 0
    1000    .044       0  1454.5    .034       0  1805.5    .044       0
#Block Obstruct= 2 , 0
         1140.51
Bank Sta=1454.5,1805.5
Sediment Elevation=0
Exp/Cntr=0.3,0.1

Type RM Length L Ch R = 1 ,29092   ,154,154,154
BEGIN DESCRIPTION:
Spur 10R
END DESCRIPTION:
#Sta/Elev= 7
     655  5399.2   661.7  5398.6    1068  5398.6    1084  5390.6    1376  5390.6
    1392  5398.6  1409.8  5398.6
#Mann= 3 , 0 , 0
     655    .044       0    1068    .034       0    1392    .044       0
Bank Sta=1068,1392
Sediment Elevation=0
Exp/Cntr=0.3,0.1

Type RM Length L Ch R = 1 ,28938   ,154,154,154
BEGIN DESCRIPTION:
Spur 9L
END DESCRIPTION:
#Sta/Elev= 19
       0  5396.6   398.5  5396.6   414.5  5388.6   685.5  5388.6   701.5  5396.6
  1025.8  5396.6  1045.5  5397.6  1077.5  5399.5  1079.5  5399.6  1093.7  5400.3
  1111.8  5401.9  1116.8  5402.3  1121.6  5402.5  1133.6  5402.8  1145.6  5403.4
    1157  5404.2    1176    5405  1205.1  5405.2  1209.1  5405.2
#Mann= 3 , 0 , 0
       0    .044       0   398.5    .034       0   701.5    .044       0
#Block Obstruct= 2 , 0
                          1386.4
Bank Sta=398.5,701.5
Sediment Elevation=0
Exp/Cntr=0.3,0.1

Type RM Length L Ch R = 1 ,28784   ,399,399,399
BEGIN DESCRIPTION:
Spur9R
END DESCRIPTION:
#Sta/Elev= 13
     655  5399.2     680  5397.2     700  5396.7     740  5397.2     770  5397.2
     820  5395.2   861.2  5394.6  1075.5  5394.6  1091.5  5386.6  1368.5  5386.6
  1384.5  5394.6  1386.1  5394.6  1387.8  5395.1
#Mann= 3 , 0 , 0
     655    .044       0  1075.5    .034       0  1384.5    .044       0
#Block Obstruct= 2 , 0
                          1386.4
Bank Sta=1075.5,1384.5
Sediment Elevation=0
Exp/Cntr=0.3,0.1

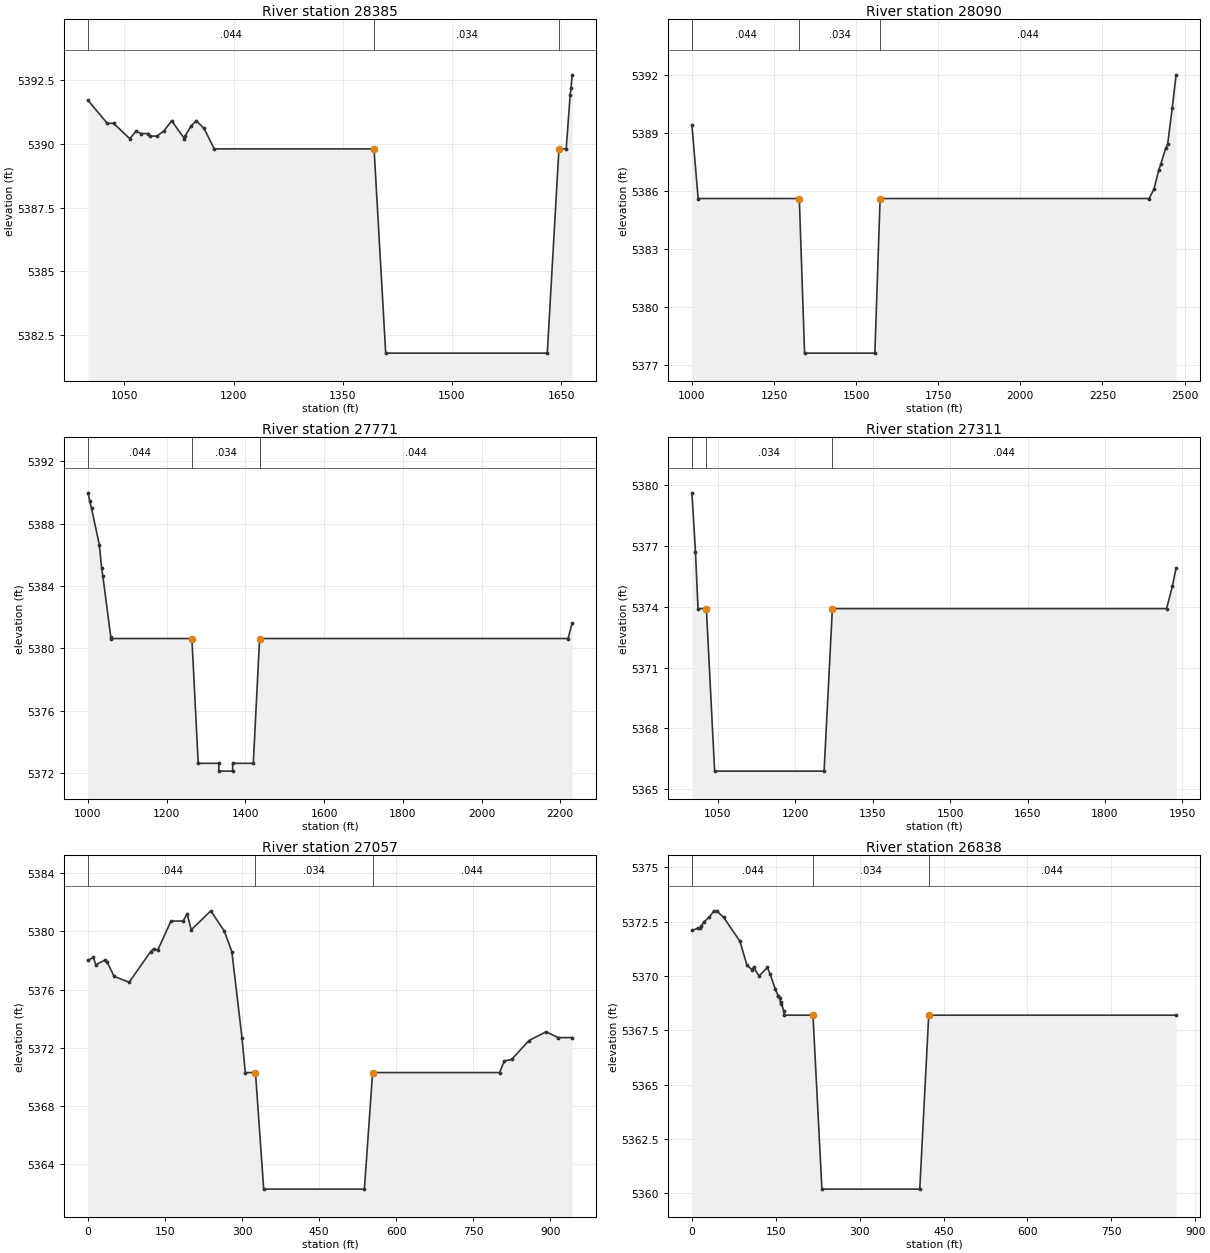
Type RM Length L Ch R = 1 ,28385   ,285,295,310
BEGIN DESCRIPTION:
Spur 8L,R
END DESCRIPTION:
#Sta/Elev= 25
    1000  5391.7  1026.5  5390.8  1035.2  5390.8  1057.3  5390.2  1066.3  5390.5
  1072.4  5390.4  1082.7  5390.4  1085.6  5390.3  1094.6  5390.3  1104.2  5390.5
    1115  5390.9  1132.5  5390.2  1133.3  5390.3  1141.7  5390.7  1148.8  5390.9
  1159.5  5390.6  1173.4  5389.8    1393  5389.8    1409  5381.8    1631  5381.8
    1647  5389.8    1657  5389.8  1662.4  5391.9  1663.7  5392.2  1665.2  5392.7
#Mann= 3 , 0 , 0
    1000    .044       0    1393    .034       0    1647    .044       0
Bank Sta=1393,1647
Sediment Elevation=0
Exp/Cntr=0.3,0.1

Type RM Length L Ch R = 1 ,28090   ,319,319,319
BEGIN DESCRIPTION:
Spur 7L
END DESCRIPTION:
#Sta/Elev= 14
    1000  5389.4    1019  5385.6    1327  5385.6    1343  5377.6    1557  5377.6
    1573  5385.6    2392  5385.6    2407  5386.1  2421.7  5387.1    2428  5387.4
  2442.3  5388.2  2448.3  5388.4  2462.5  5390.3  2474.1    5392
#Mann= 3 , 0 , 0
    1000    .044       0    1327    .034       0    1573    .044       0
#Block Obstruct= 2 , 0
                            1600
Bank Sta=1327,1573
Sediment Elevation=0
Exp/Cntr=0.3,0.1

Type RM Length L Ch R = 1 ,27771   ,530,460,430
BEGIN DESCRIPTION:
GCS4 Crest
END DESCRIPTION:
#Sta/Elev= 18
    1000 5389.97 1004.07 5389.47 1009.06 5388.97 1028.76 5386.64 1034.74 5385.13
 1037.66 5384.64 1057.96 5380.72 1058.37 5380.63    1264 5380.63    1280 5372.63
  1332.5 5372.63  1332.5 5372.13  1367.5 5372.13  1367.5 5372.63    1420 5372.63
    1436 5380.63 2219.91 5380.63 2230.28 5381.63
#Mann= 3 , 0 , 0
    1000    .044       0    1264    .034       0    1436    .044       0
Bank Sta=1264,1436
Sediment Elevation=0
Exp/Cntr=0.3,0.1

Type RM Length L Ch R = 1 ,27311   ,254,254,254
BEGIN DESCRIPTION:
Spur6L
END DESCRIPTION:
#Sta/Elev= 10
    1000  5379.6  1006.9  5376.7  1011.8  5373.9    1028  5373.9    1044  5365.9
    1256  5365.9    1272  5373.9  1919.3  5373.9  1930.5    5375  1937.7  5375.9
#Mann= 3 , 0 , 0
    1000    .044       0    1028    .034       0    1272    .044       0
Bank Sta=1028,1272
Sediment Elevation=0
Exp/Cntr=0.3,0.1

Type RM Length L Ch R = 1 ,27057   ,219,219,219
BEGIN DESCRIPTION:
Spur 5L,R
END DESCRIPTION:
#Sta/Elev= 30
       0    5378    10.6  5378.2    15.1  5377.7    32.2    5378      37  5377.9
    50.8  5376.9    80.1  5376.5   121.9  5378.6     128  5378.8   135.7  5378.7
   161.6  5380.7   185.2  5380.7   192.8  5381.2   201.1  5380.1   239.1  5381.4
   265.5    5380     280  5378.6   299.7  5372.7   306.2  5370.3     326  5370.3
     342  5362.3     538  5362.3     554  5370.3   801.1  5370.3   810.5  5371.1
   824.5  5371.2   858.5  5372.5   891.8  5373.1   915.1  5372.7   942.5  5372.7
#Mann= 3 , 0 , 0
       0    .044       0     326    .034       0     554    .044       0
Bank Sta=326,554
Sediment Elevation=0
Exp/Cntr=0.3,0.1

Type RM Length L Ch R = 1 ,26838   ,73,73,73
BEGIN DESCRIPTION:
Spur4R
END DESCRIPTION:
#Sta/Elev= 29
       0  5372.1    11.2  5372.2    14.9  5372.2    17.1  5372.3    21.6  5372.5
    30.9  5372.7    39.4    5373      44    5373    56.8  5372.7    85.9  5371.6
    98.4  5370.5   107.1  5370.3   110.4  5370.4   120.1    5370     135  5370.4
   139.7  5370.1   149.1  5369.4     154  5369.1   154.3  5369.1   156.9    5369
   159.1  5368.7   159.4  5368.8   164.2  5368.4   165.1  5368.2   216.5  5368.2
   232.5  5360.2   407.5  5360.2   423.5  5368.2   865.9  5368.2
#Mann= 3 , 0 , 0
       0    .044       0   216.5    .034       0   423.5    .044       0
Bank Sta=216.5,423.5
Sediment Elevation=0
Exp/Cntr=0.3,0.1

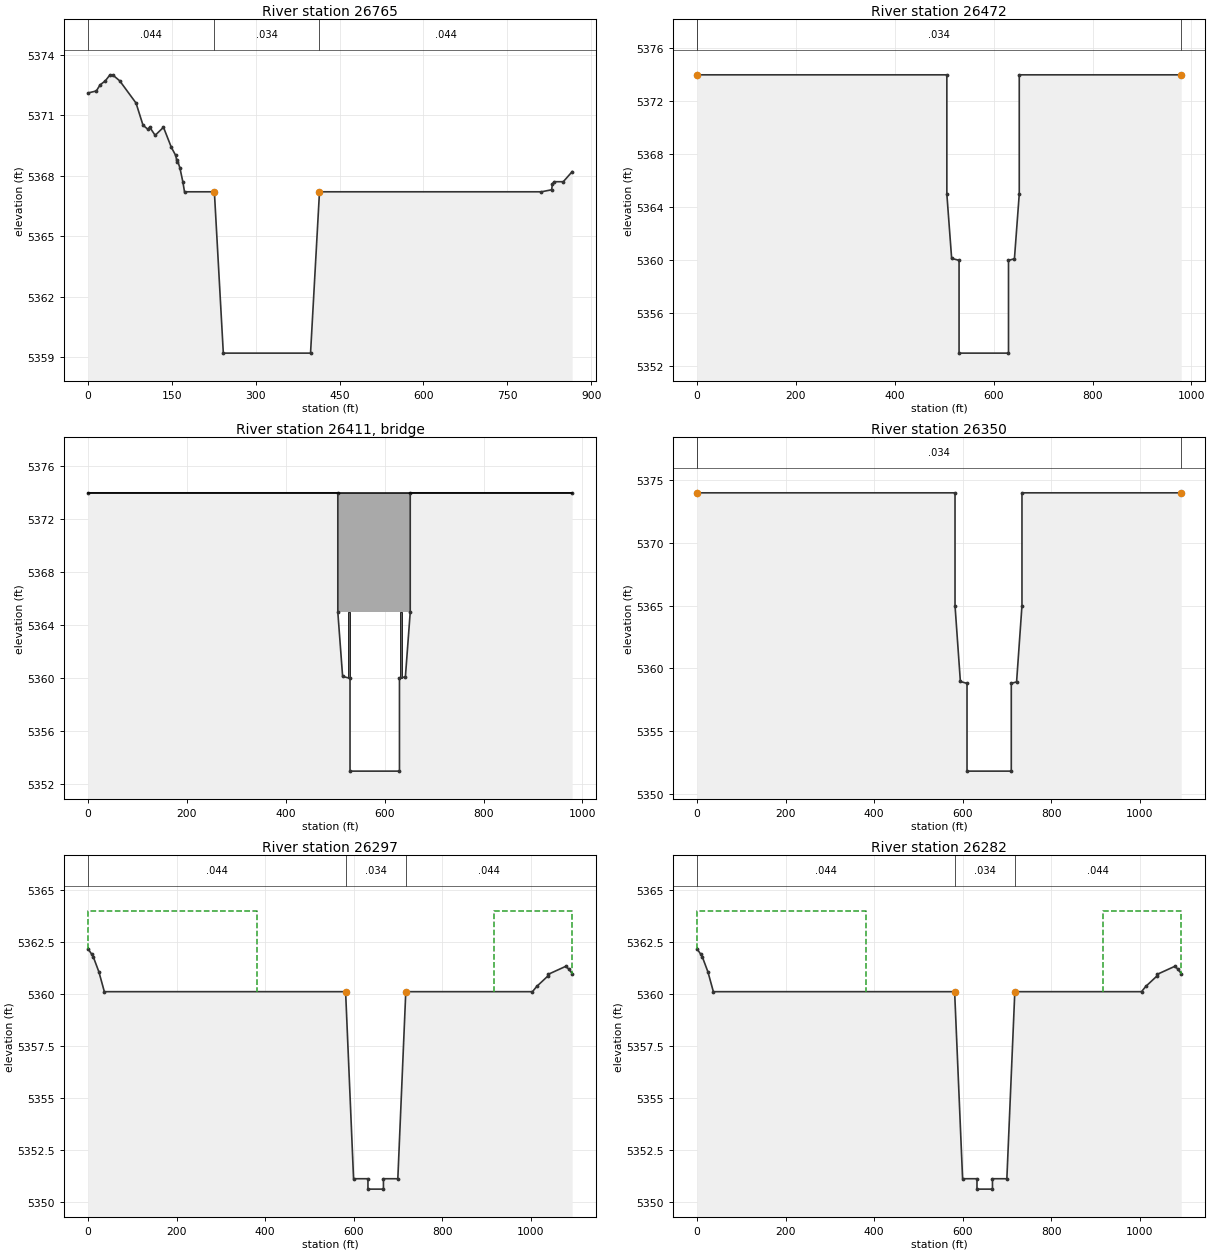
Type RM Length L Ch R = 1 ,26765   ,293,293,305
BEGIN DESCRIPTION:
Spur 4L
END DESCRIPTION:
#Sta/Elev= 30
       0  5372.1    14.9  5372.2    21.6  5372.5    30.9  5372.7    39.4    5373
      44    5373    56.8  5372.7    85.9  5371.6    98.4  5370.5   107.1  5370.3
   110.4  5370.4   120.1    5370     135  5370.4   149.1  5369.4   156.9    5369
   159.1  5368.7   159.4  5368.8   164.2  5368.4   169.6  5367.7   172.6  5367.2
     226  5367.2     242  5359.2     398  5359.2     414  5367.2     811  5367.2
   829.1  5367.3   830.7  5367.6   833.8  5367.7     850  5367.7   865.9  5368.2
#Mann= 3 , 0 , 0
       0    .044       0     226    .034       0     414    .044       0
Bank Sta=226,414
Exp/Cntr=0.3,0.1

Type RM Length L Ch R = 1 ,26472   ,122,122,122
BEGIN DESCRIPTION:
US Brg
END DESCRIPTION:
#Sta/Elev= 12
       0    5374   505.3    5374   505.3    5365     515 5360.15     530    5360
     530    5353     630    5353     630    5360     642 5360.12  651.76    5365
  651.76    5374  979.33    5374
#Mann= 3 , 0 , 0
       0    .044       0       0    .034       0  979.33    .044       0
Bank Sta=0,979.33
Sediment Elevation=0
Exp/Cntr=0.5,0.3

Type RM Length L Ch R = 3 ,26411   ,,,
BEGIN DESCRIPTION:
McMahon Bridge Crossing
END DESCRIPTION:
Bridge Culvert--1,0,-1,-1, 0
Deck Dist Width WeirC Skew NumUp NumDn MinLoCord MaxHiCord MaxSubmerge Is_Ogee
1,120,2.6,0, 2, 2, , , 0.95, 0, 0,0,,
       0  979.33
    5374    5374
    5365    5365
       0 1093.93
    5374    5374
    5365    5365
Pier Skew, UpSta & Num, DnSta & Num=  ,527.5, 4 ,607.5, 4 , 3 , 3 , 0 ,,
       4       4     4.5     4.5
    5353    5360    5360    5365
       4       4     4.5     4.5
 5351.94 5358.94 5358.94    5365
Pier Skew, UpSta & Num, DnSta & Num=  ,632.5, 4 ,712.5, 4 , 3 , 3 , 0 ,,
       4       4     4.5     4.5
    5353    5360    5360    5365
       4       4     4.5     4.5
 5351.94 5358.94 5358.94    5365
BR Coef=-1 , 0 , 0 ,, 0 ,,,0.8,-1,,0,
WSPro=,,,, 1 ,,,, 0 ,,,, 0 ,,,,-1 ,-1 ,-1 , 0 , 0 , 0 , 0 , 0
BC Design=5374,5365, 0 ,, 0 ,,,,,,

Type RM Length L Ch R = 1 ,26350   ,53,53,53
BEGIN DESCRIPTION:
DS Brg
END DESCRIPTION:
#Sta/Elev= 12
       0    5374   582.9    5374   582.9    5365     595 5358.95     610  5358.8
     610  5351.8     710  5351.8     710  5358.8     722 5358.92  734.16    5365
  734.16    5374 1093.93    5374
#Mann= 3 , 0 , 0
       0    .044       0       0    .034       0 1093.93    .044       0
Bank Sta=0,1093.93
Sediment Elevation=0
Exp/Cntr=0.5,0.3

Type RM Length L Ch R = 1 ,26297   ,15,15,15
BEGIN DESCRIPTION:
GCS3 U/S Sill (Flat across sill)
END DESCRIPTION:
#Sta/Elev= 20
       0 5362.17     8.2 5361.92   12.23 5361.77   24.66 5361.06   36.91 5360.11
     582 5360.11     600 5351.11   632.5 5351.11   632.5 5350.61   667.5 5350.61
   667.5 5351.11     700 5351.11     718 5360.11 1004.21 5360.11 1013.73 5360.36
 1038.91 5360.86 1040.29 5360.95 1079.44 5361.33  1085.8 5361.21 1093.91 5360.98
#Mann= 3 , 0 , 0
       0    .044       0     582    .034       0     718    .044       0
#XS Ineff= 2 , 0
       0     382    5364     918       0    5364
Permanent Ineff=
       T       T
Bank Sta=582,718
Sediment Elevation=0
Exp/Cntr=0.3,0.1

Type RM Length L Ch R = 1 ,26282   ,251,303,318
BEGIN DESCRIPTION:
GCS3 Crest
END DESCRIPTION:
#Sta/Elev= 20
       0 5362.17     8.2 5361.92   12.23 5361.77   24.66 5361.06   36.91 5360.11
     582 5360.11     600 5351.11   632.5 5351.11   632.5 5350.61   667.5 5350.61
   667.5 5351.11     700 5351.11     718 5360.11 1004.21 5360.11 1013.73 5360.36
 1038.91 5360.86 1040.29 5360.95 1079.44 5361.33  1085.8 5361.21 1093.91 5360.98
#Mann= 3 , 0 , 0
       0    .044       0     582    .034       0     718    .044       0
#XS Ineff= 2 , 0
       0     382    5364     918       0    5364
Permanent Ineff=
       T       T
Bank Sta=582,718
Sediment Elevation=0
Exp/Cntr=0.3,0.1