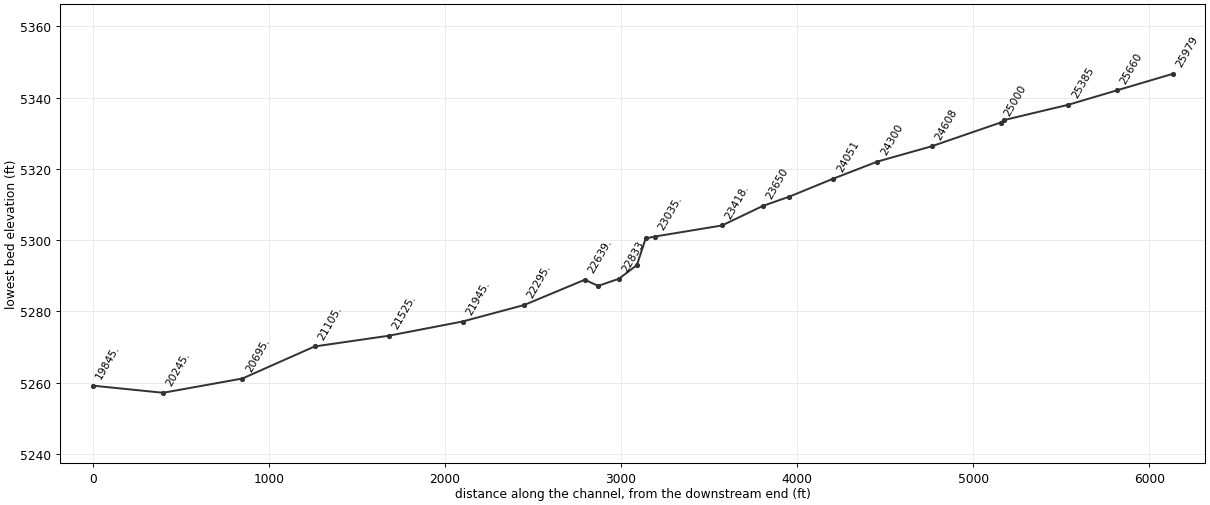
HEC-RAS study NBCalab.prj: North Branch Calabacillas Arroyo

--- NBCalab.g03 (geometry) --- (continued)

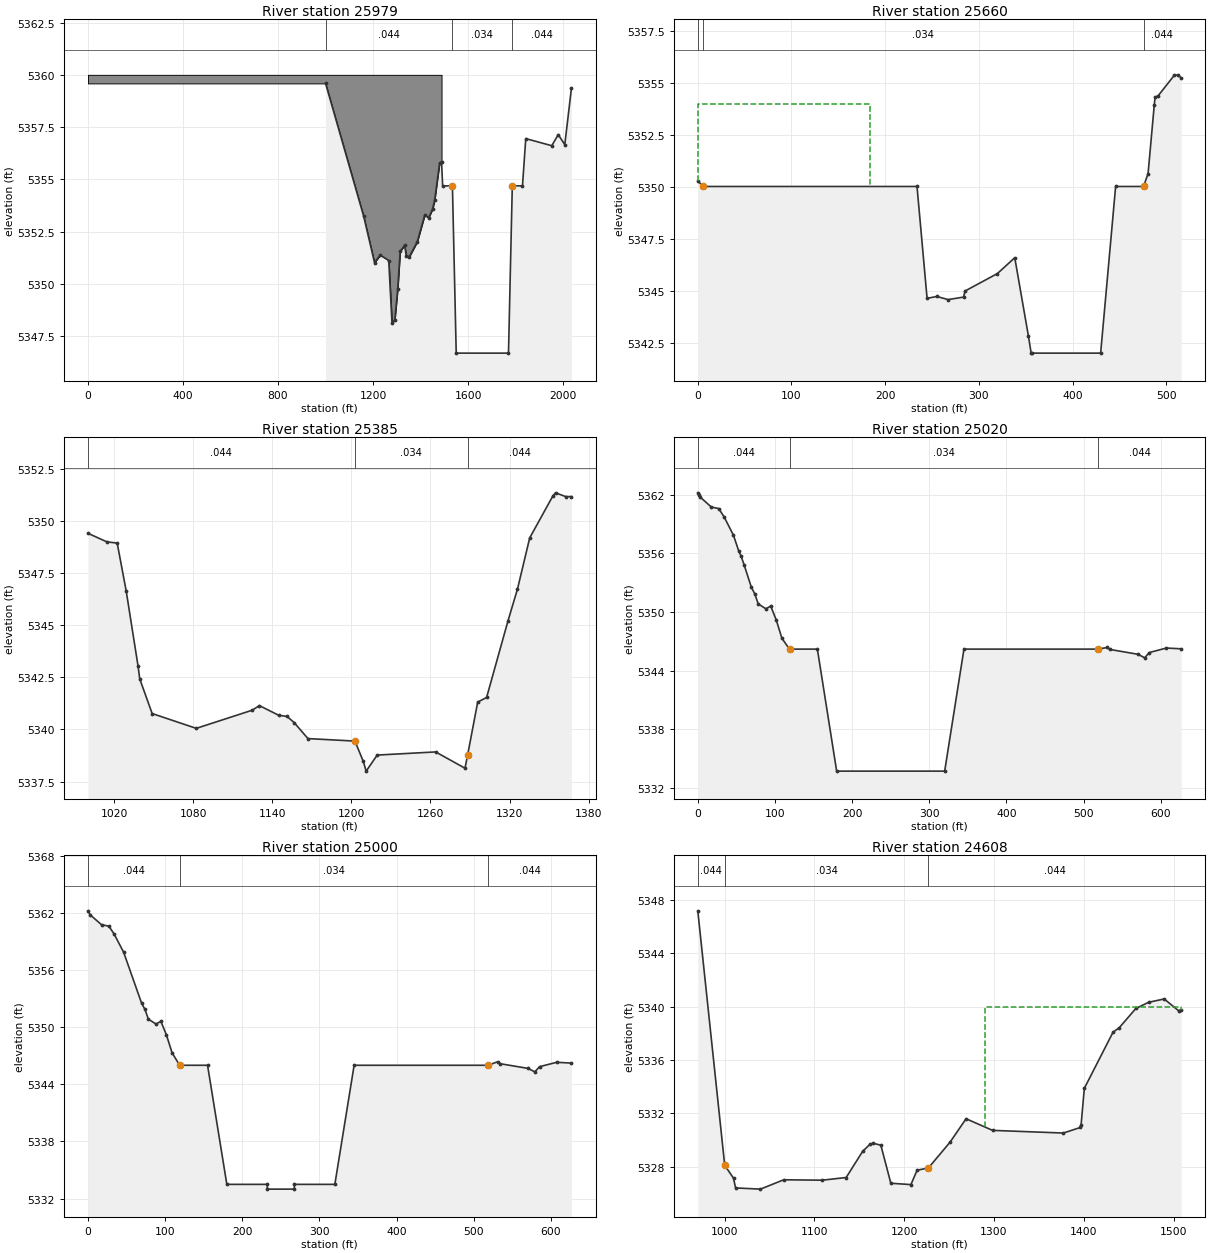
Type RM Length L Ch R = 1 ,25979   ,295,319,371
BEGIN DESCRIPTION:
Fill Section at 25979
END DESCRIPTION:
#Sta/Elev= 30
    1000 5359.59 1160.58 5353.23 1206.02 5351.02 1230.24 5351.38 1265.92 5351.12
  1279.6 5348.14  1291.4 5348.26 1303.82 5349.76 1314.05 5351.56 1332.71 5351.84
 1339.63 5351.35 1352.54  5351.3 1386.17 5352.02 1417.64  5353.3 1433.74 5353.16
 1450.47 5353.58 1459.32 5354.01    1480 5355.78 1488.18 5355.84 1492.88 5354.69
    1534 5354.69    1550 5346.69    1770 5346.69    1786 5354.69 1828.85 5354.69
 1842.67 5356.95 1952.08 5356.61 1979.44 5357.14 2006.92 5356.66 2034.82 5359.35
#Mann= 3 , 0 , 0
    1000    .044       0    1534    .034       0    1786    .044       0
#Block Obstruct= 2 , 0
       0 1488.18    5360               0
Bank Sta=1534,1786
Sediment Elevation=0
Exp/Cntr=0.3,0.1

Type RM Length L Ch R = 1 ,25660   ,317,275,250
BEGIN DESCRIPTION:
Spur3, rb represents d/s limit of rb riprap
END DESCRIPTION:
#Sta/Elev= 23
       0 5350.31    5.39 5350.03     234 5350.03  244.74 5344.66  255.15 5344.75
  267.14  5344.6  283.71 5344.72  285.17 5345.01  319.81 5345.85  338.33 5346.61
  352.98 5342.83  355.76 5342.05  356.45 5342.03     430 5342.03     446 5350.03
   475.8 5350.03  480.63 5350.65  487.26 5353.95  488.17 5354.33  490.94 5354.36
  508.49 5355.36  512.99 5355.39  516.03 5355.22
#Mann= 3 , 0 , 0
       0    .044       0    5.39    .034       0   475.8    .044       0
#XS Ineff= 2 , 0
       0     184    5354               0
Permanent Ineff=
       T       F
Bank Sta=5.39,475.8
Sediment Elevation=0
Exp/Cntr=0.3,0.1

Type RM Length L Ch R = 1 ,25385   ,417,365,335
BEGIN DESCRIPTION:
Existing Section, no fill necessary
END DESCRIPTION:
#Sta/Elev= 30
    1000  5349.4 1014.34 5348.99 1022.19 5348.93 1029.01 5346.64 1038.04 5343.03
  1039.3 5342.42 1048.73 5340.76 1082.22 5340.05 1124.66 5340.92 1130.14 5341.14
 1144.72 5340.68 1151.14 5340.62 1156.49 5340.33 1166.99 5339.56 1202.64 5339.44
 1208.92 5338.48 1211.19    5338 1219.57 5338.77 1263.94 5338.92 1286.21 5338.14
 1288.26 5338.79 1295.85 5341.31 1302.61 5341.53 1318.79 5345.19 1326.06 5346.73
 1335.33 5349.18    1353  5351.2 1354.94 5351.34 1362.63 5351.16 1366.99 5351.16
#Mann= 3 , 0 , 0
    1000    .044       0 1202.64    .034       0 1288.26    .044       0
Bank Sta=1202.64,1288.26
Sediment Elevation=0
Exp/Cntr=0.3,0.1

Type RM Length L Ch R = 1 ,25020   ,20,20,20
BEGIN DESCRIPTION:
GCS2 Inlet
END DESCRIPTION:
#Sta/Elev= 30
       0 5362.21    2.18 5362.02    2.61 5361.81   17.59 5360.75    27.1  5360.6
   34.02 5359.76   46.26 5357.86   53.02 5356.26   56.23  5355.7   59.97 5354.85
   69.49 5352.52   73.89 5351.86   78.26 5350.84   88.24 5350.33   94.51 5350.61
  101.64  5349.2  109.07  5347.3  118.88  5346.2     155  5346.2     180  5333.7
     320  5333.7     345  5346.2  518.84  5346.2  530.99 5346.37  533.77 5346.17
  570.56 5345.67  579.18 5345.31  585.32 5345.85   607.4 5346.31  626.63 5346.23
#Mann= 3 , 0 , 0
       0    .044       0  118.88    .034       0  518.84    .044       0
Bank Sta=118.88,518.84
Sediment Elevation=0
Exp/Cntr=0.3,0.1

Type RM Length L Ch R = 1 ,25000   ,480,392,280
BEGIN DESCRIPTION:
GCS2 Crest
END DESCRIPTION:
#Sta/Elev= 30
       0 5362.21    2.61 5361.81   17.59 5360.75    27.1  5360.6   34.02 5359.76
   46.26 5357.86   69.49 5352.52   73.89 5351.86   78.26 5350.84   88.24 5350.33
   94.51 5350.61  101.64  5349.2  109.07  5347.3  118.88    5346     155    5346
     180  5333.5   232.5  5333.5   232.5    5333   267.5    5333   267.5  5333.5
     320  5333.5     345    5346  518.84    5346  530.99 5346.37  533.77 5346.17
  570.56 5345.67  579.18 5345.31  585.32 5345.85   607.4 5346.31  626.63 5346.23
#Mann= 3 , 0 , 0
       0    .044       0  118.88    .034       0  518.84    .044       0
Bank Sta=118.88,518.84
Sediment Elevation=0
Exp/Cntr=0.3,0.1

Type RM Length L Ch R = 1 ,24608   ,320,308,300
BEGIN DESCRIPTION:
Cut from Goodwin (2003) Mapping
END DESCRIPTION:
#Sta/Elev= 30
     970 5347.17    1000 5328.11 1009.78 5327.15 1012.09 5326.42 1039.76 5326.33
 1065.77 5327.03 1108.88    5327 1135.28  5327.2 1153.68 5329.16 1162.17 5329.71
 1165.58 5329.76 1173.95 5329.62 1185.06 5326.77 1207.44 5326.67 1214.35 5327.75
 1226.84 5327.91 1251.08 5329.85 1268.89  5331.6  1298.4 5330.73 1377.25 5330.53
 1396.35 5330.95 1397.01 5331.13 1400.64 5333.88 1432.52 5338.07 1439.71 5338.43
 1458.07 5339.86 1472.24 5340.32  1489.6 5340.57 1505.61 5339.69  1508.6 5339.77
#Mann= 3 , 0 , 0
     970    .044       0    1000    .034       0 1226.84    .044       0
#XS Ineff= 2 , 0
       0                    1290       0    5340
Permanent Ineff=
       F       T
Bank Sta=1000,1226.84
Exp/Cntr=0.3,0.1

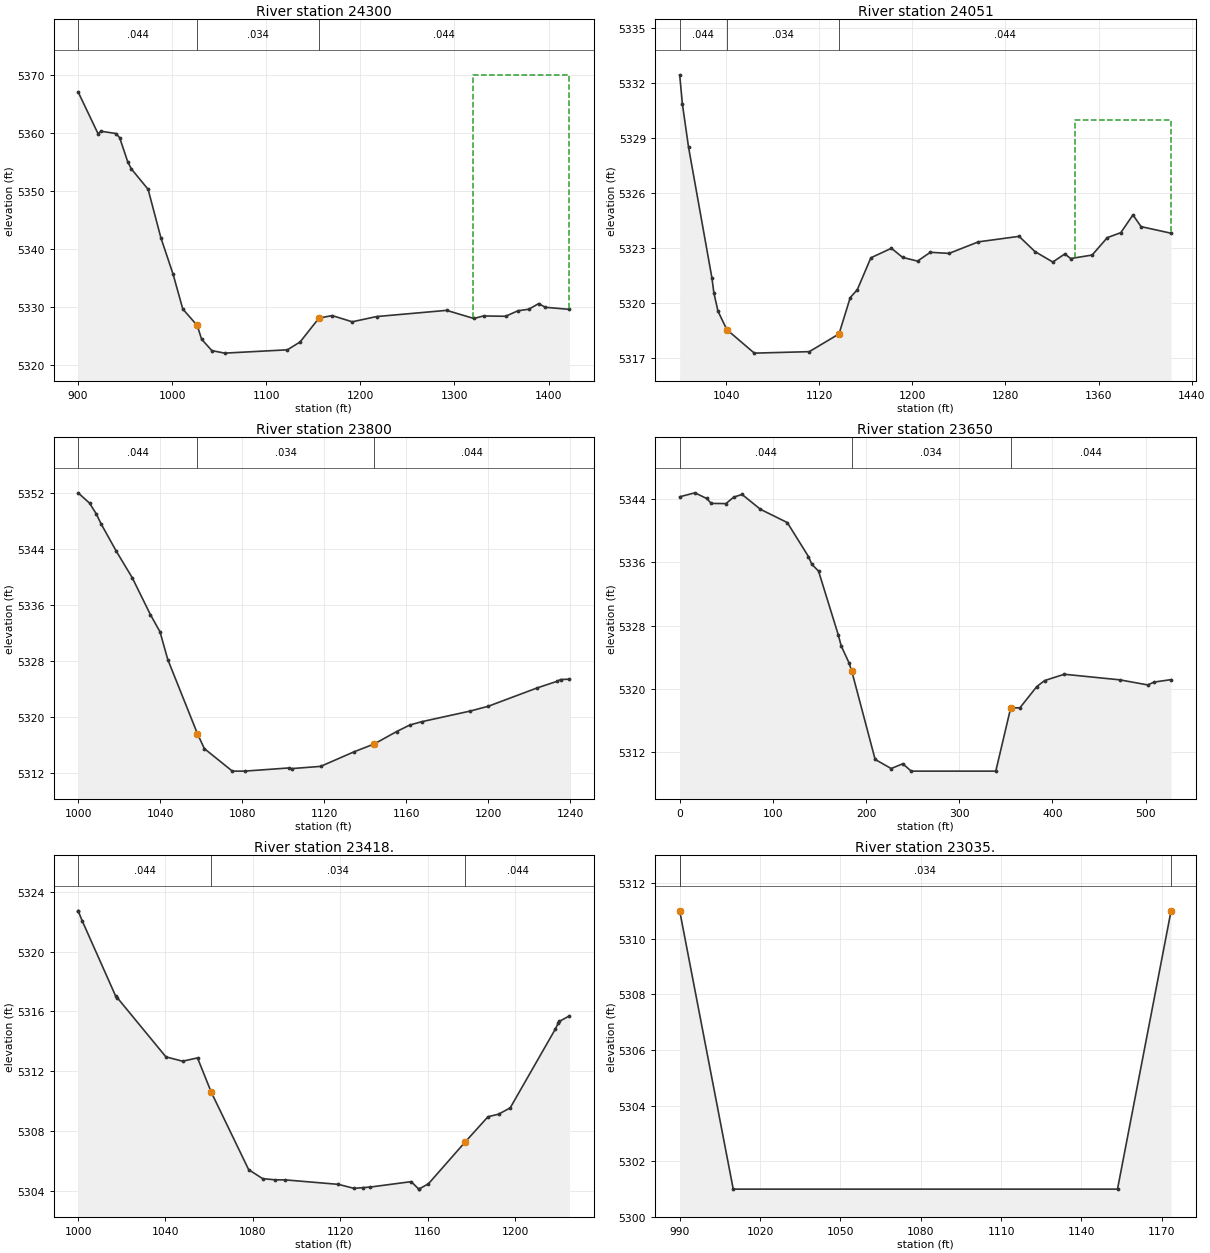
Type RM Length L Ch R = 1 ,24300   ,388,249,160
BEGIN DESCRIPTION:
Spur2 - removed per Dan's email on 2/10/05
END DESCRIPTION:
#Sta/Elev= 30
     900 5367.06  921.26 5359.83  924.25 5360.28  940.37 5359.88   944.2 5359.15
  952.65 5355.06  956.52  5353.8   974.4 5350.27  987.98 5341.92 1000.94 5335.65
 1011.28 5329.64 1026.57 5326.81 1031.25 5324.45 1042.17 5322.47 1055.85 5322.04
 1122.42 5322.61 1135.99 5323.97 1156.03 5328.08 1170.08 5328.51 1191.35 5327.44
 1217.19 5328.34 1291.71 5329.41 1320.65 5328.01 1330.99 5328.45 1354.46 5328.39
 1367.49 5329.34 1379.09 5329.61 1389.55 5330.58 1396.52 5329.94  1422.3 5329.58
#Mann= 3 , 0 , 0
     900    .044       0 1026.57    .034       0 1156.03    .044       0
#XS Ineff= 2 , 0
       0                    1320       0    5370
Permanent Ineff=
       F       T
Bank Sta=1026.57,1156.03
Sediment Elevation=0
Exp/Cntr=0.3,0.1

Type RM Length L Ch R = 1 ,24051   ,350,251,150
BEGIN DESCRIPTION:
From BHI (2000) Mapping, adjusted to VD29
END DESCRIPTION:
#Sta/Elev= 30
    1000 5332.45 1002.34 5330.85 1007.65 5328.49 1027.71 5321.37  1029.4 5320.55
  1032.9 5319.56 1040.53 5318.55 1064.15 5317.27 1111.39 5317.35 1136.95 5318.32
 1146.57  5320.3 1152.65 5320.73  1164.3 5322.47 1181.98 5322.99 1191.63 5322.49
 1204.39 5322.29 1215.41 5322.77 1231.51 5322.71 1256.71 5323.34 1291.71 5323.64
  1305.3 5322.81 1320.65 5322.24 1330.99 5322.68 1336.02 5322.43 1354.46 5322.62
 1367.49 5323.57 1379.09 5323.84 1389.55 5324.81 1396.52 5324.17  1422.3 5323.81
#Mann= 3 , 0 , 0
    1000    .044       0 1040.53    .034       0 1136.95    .044       0
#XS Ineff= 2 , 0
       0                    1340       0    5330
Permanent Ineff=
       F       T
Bank Sta=1040.53,1136.95
Exp/Cntr=0.3,0.1

Type RM Length L Ch R = 1 ,23800   ,150,150,150
BEGIN DESCRIPTION:
Existing 23800 - u/s limit of caliche
END DESCRIPTION:
#Sta/Elev= 27
    1000 5351.97 1005.61 5350.49 1008.87 5348.95 1011.18 5347.55 1018.66 5343.61
 1026.41 5339.83 1035.23 5334.58 1039.94  5332.1 1043.72 5328.15 1058.17 5317.56
 1061.55 5315.42  1075.2  5312.2 1081.15  5312.2 1103.06 5312.66 1104.05 5312.56
 1118.27 5312.88 1134.54 5314.96 1144.37 5316.08 1155.33 5317.86 1161.82  5318.8
 1167.65 5319.27 1191.27 5320.79 1199.99 5321.47 1223.92  5324.1 1233.69 5325.05
 1235.24 5325.29  1239.6 5325.34
#Mann= 3 , 0 , 0
    1000    .044       0 1058.17    .034       0 1144.37    .044       0
Bank Sta=1058.17,1144.37
Sediment Elevation=0
Exp/Cntr=0.3,0.1

Type RM Length L Ch R = 1 ,23650   ,230,232,230
BEGIN DESCRIPTION:
Spur1
END DESCRIPTION:
#Sta/Elev= 30
       0 5344.29   16.32 5344.79   28.87 5344.08   33.97 5343.45   49.65 5343.43
   57.95 5344.24   66.89 5344.59   86.63 5342.71  115.48 5341.03  138.21 5336.73
  141.81 5335.75  148.99  5334.9  170.27  5326.8  173.31 5325.44  181.57 5323.33
  184.58 5322.28  209.74 5311.08  226.93 5309.93  239.43 5310.53  248.47  5309.6
  339.22  5309.6  355.22  5317.6  365.06  5317.6  383.28  5320.3  391.59 5321.05
  412.73 5321.85  472.49 5321.14  502.29  5320.5  509.12 5320.86  527.32 5321.17
#Mann= 3 , 0 , 0
       0    .044       0  184.58    .034       0  355.22    .044       0
Bank Sta=184.58,355.22
Sediment Elevation=0
Exp/Cntr=0.3,0.1

Type RM Length L Ch R = 1 ,23418.  ,363,383,411
BEGIN DESCRIPTION:
Existing Section
END DESCRIPTION:
#Sta/Elev= 29
    1000 5322.72 1000.03 5322.71 1001.94 5322.03 1017.17 5317.03 1017.94 5316.91
 1040.19 5312.96 1047.83 5312.67 1054.66 5312.89 1060.98 5310.59 1078.09 5305.42
  1084.5 5304.82 1090.29 5304.74 1094.65 5304.74 1119.13 5304.44 1126.33 5304.17
 1130.32 5304.22 1133.83 5304.26 1152.48 5304.62 1155.97 5304.12 1155.99 5304.12
 1160.41 5304.48 1177.32 5307.29 1187.66 5308.96 1192.49 5309.13 1197.81 5309.55
 1218.37 5314.79 1219.89 5315.24 1220.28 5315.33 1224.96  5315.7
#Mann= 3 , 0 , 0
    1000    .044       0 1060.98    .034       0 1177.32    .044       0
Bank Sta=1060.98,1177.32
Sediment Elevation=0
Exp/Cntr=0.3,0.1

Type RM Length L Ch R = 1 ,23035.  ,49,50,50
BEGIN DESCRIPTION:
CGW230.35 - GCS inlet (modified to as-blt)
END DESCRIPTION:
#Sta/Elev= 4
     990    5311    1010    5301  1153.5    5301  1173.5    5311
#Mann= 3 , 0 , 0
     990    .044       0     990    .034       0  1173.5    .044       0
Bank Sta=990,1173.5
Exp/Cntr=0.3,0.1

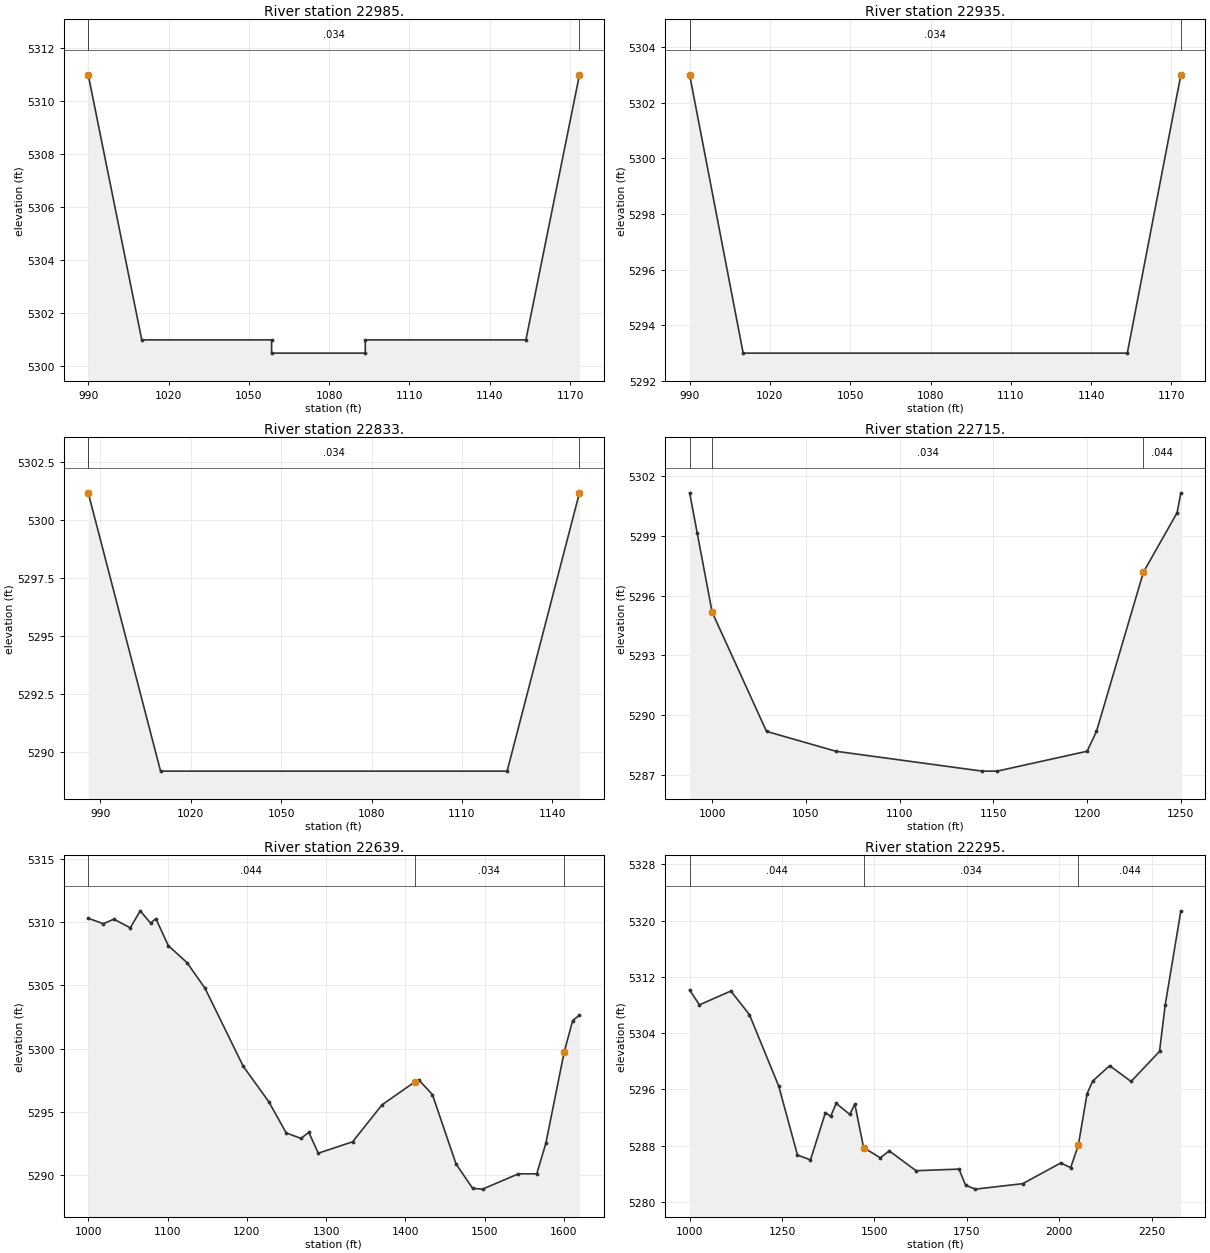
Type RM Length L Ch R = 1 ,22985.  ,48,50,50
BEGIN DESCRIPTION:
CGW229.85 - GCS Crest (modified to as-blt)
END DESCRIPTION:
#Sta/Elev= 8
     990    5311    1010    5301  1058.5    5301  1058.5  5300.5  1093.5  5300.5
  1093.5    5301  1153.5    5301  1173.5    5311
#Mann= 3 , 0 , 0
     990    .044       0     990    .034       0  1173.5    .044       0
Bank Sta=990,1173.5
Exp/Cntr=0.3,0.1

Type RM Length L Ch R = 1 ,22935.  ,97,102,102
BEGIN DESCRIPTION:
CGW229.35 - GCS exit
END DESCRIPTION:
#Sta/Elev= 4
     990    5303    1010    5293  1153.5    5293  1173.5    5303
#Mann= 3 , 0 , 0
     990    .044       0     990    .034       0  1173.5    .044       0
Bank Sta=990,1173.5
Exp/Cntr=0.3,0.1

Type RM Length L Ch R = 1 ,22833.  ,112,118,118
BEGIN DESCRIPTION:
CGW228.33-115' wide base width to approx excavation
END DESCRIPTION:
#Sta/Elev= 4
     986 5301.17    1010 5289.17    1125 5289.17    1149 5301.17
#Mann= 3 , 0 , 0
     986    .044       0     986    .034       0    1149    .044       0
Bank Sta=986,1149
Exp/Cntr=0.3,0.1

Type RM Length L Ch R = 1 ,22715.  ,73,76,76
BEGIN DESCRIPTION:
CGW 22715, GCS Model
END DESCRIPTION:
#Sta/Elev= 12
     988 5301.17     992 5299.17    1000 5295.17    1029 5289.17    1066 5288.17
    1144 5287.17    1152 5287.17    1200 5288.17    1205 5289.17    1230 5297.17
    1248 5300.17    1250 5301.17
#Mann= 3 , 0 , 0
     988    .044       0    1000    .034       0    1230    .044       0
Bank Sta=1000,1230
Exp/Cntr=0.3,0.1

Type RM Length L Ch R = 1 ,22639.  ,350,344,350
#Sta/Elev= 30
    1000  5310.3 1019.06 5309.87 1032.26 5310.23 1053.08 5309.55 1065.58 5310.89
 1078.65 5309.92 1085.28 5310.27  1101.1 5308.13 1124.68 5306.79 1147.38 5304.76
 1195.42 5298.61 1227.62 5295.81 1249.74 5293.33 1268.43  5292.9 1278.23 5293.38
 1290.14 5291.73 1333.45 5292.63 1370.47 5295.55 1411.52 5297.35  1417.3  5297.5
 1434.06 5296.37 1463.91 5290.88 1484.87 5288.95 1497.44 5288.89  1542.6  5290.1
 1565.72  5290.1  1577.2 5292.52 1600.27 5299.72 1611.03 5302.22 1619.56 5302.64
#Mann= 3 , 0 , 0
    1000    .044       0 1411.52    .034       0 1600.27    .044       0
#Block Obstruct= 2 , 0
          1417.3
Bank Sta=1411.52,1600.27
Sediment Elevation=0
Exp/Cntr=0.3,0.1

Type RM Length L Ch R = 1 ,22295.  ,350,350,490
#Sta/Elev= 30
    1000 5310.13  1026.6 5308.02  1111.5 5309.99  1161.7 5306.64  1241.1 5296.45
  1291.8 5286.65    1327 5285.96  1367.5  5292.7  1381.4 5292.15  1396.6    5294
  1433.4 5292.43  1446.9 5293.91  1470.7  5287.7    1516 5286.25    1540 5287.25
  1612.5 5284.42  1728.8 5284.65  1746.6 5282.35  1773.2  5281.8  1901.3 5282.58
    2004 5285.52  2030.9 5284.86  2051.6 5288.04  2075.2 5295.37  2090.7 5297.19
  2136.4 5299.37  2194.3 5297.12  2271.3  5301.4  2286.6 5307.99    2329  5321.4
#Mann= 3 , 0 , 0
    1000    .044       0  1470.7    .034       0  2051.6    .044       0
#Block Obstruct= 2 , 0
            1600
Bank Sta=1470.7,2051.6
Sediment Elevation=0
Exp/Cntr=0.3,0.1

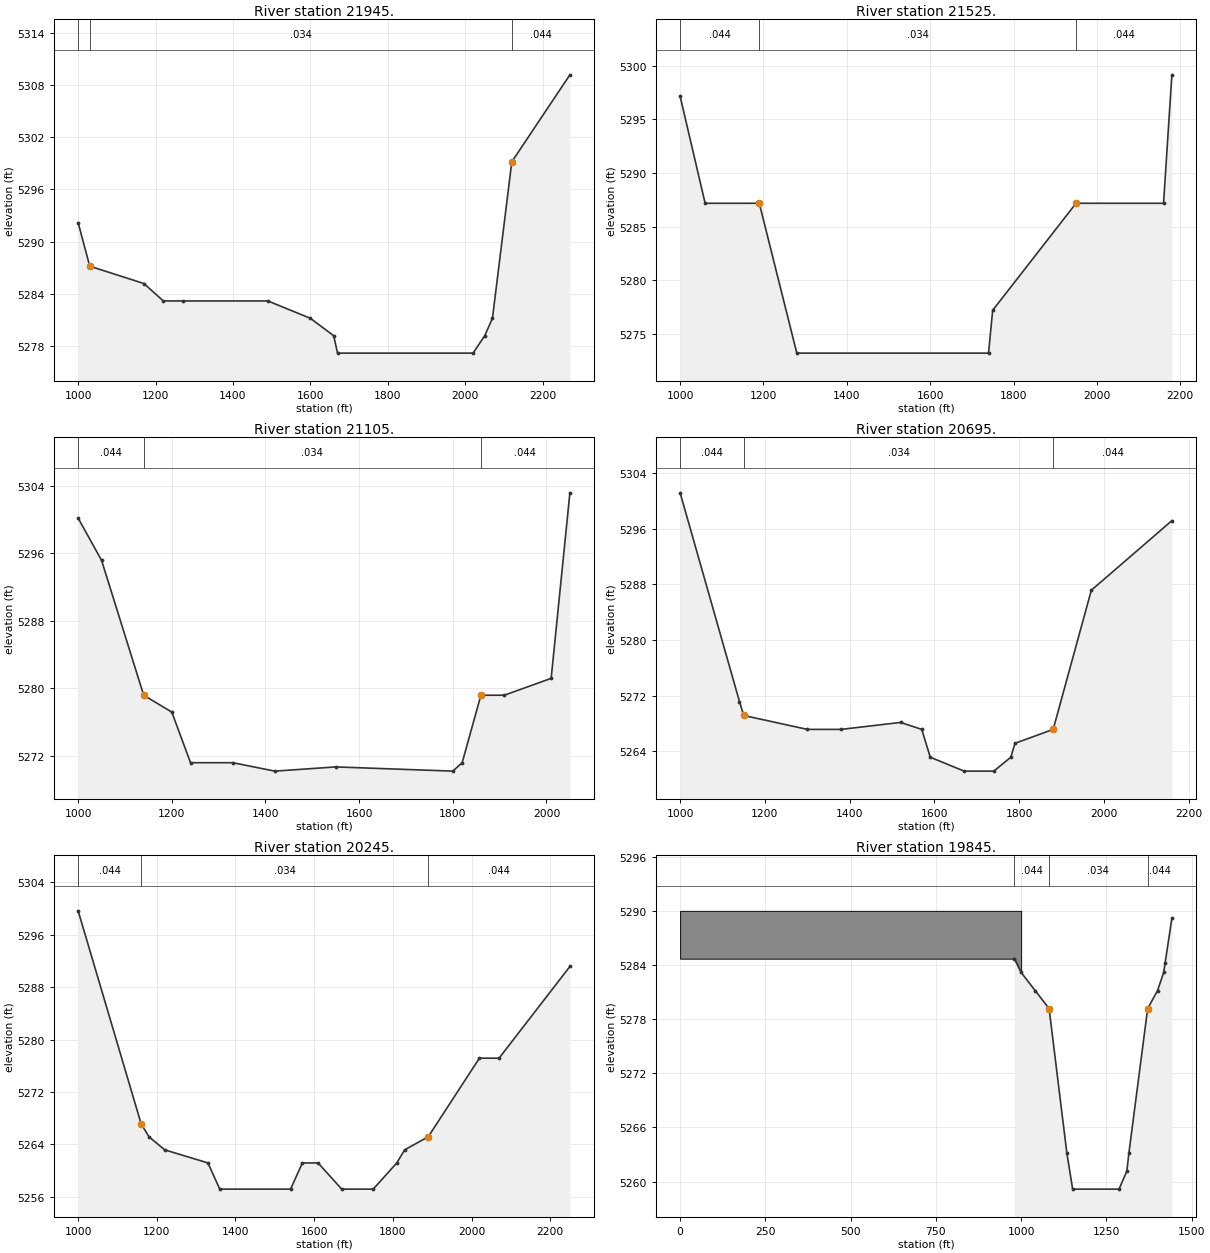
Type RM Length L Ch R = 1 ,21945.  ,260,420,460
#Sta/Elev= 14
    1000 5292.17    1030 5287.17    1170 5285.17    1220 5283.17    1270 5283.17
    1490 5283.17    1600 5281.17    1660 5279.17    1670 5277.17    2020 5277.17
    2050 5279.17    2070 5281.17    2120 5299.17    2270 5309.17
#Mann= 3 , 0 , 0
    1000    .044       0    1030    .034       0    2120    .044       0
#Block Obstruct= 2 , 0
            1450
Bank Sta=1030,2120
Sediment Elevation=0
Exp/Cntr=0.3,0.1

Type RM Length L Ch R = 1 ,21525.  ,210,420,450
#Sta/Elev= 9
    1000 5297.17    1060 5287.17    1190 5287.17    1280 5273.17    1740 5273.17
    1750 5277.17    1950 5287.17    2160 5287.17    2180 5299.17
#Mann= 3 , 0 , 0
    1000    .044       0    1190    .034       0    1950    .044       0
#Block Obstruct= 2 , 0
            1230
Bank Sta=1190,1950
Sediment Elevation=0
Exp/Cntr=0.3,0.1

Type RM Length L Ch R = 1 ,21105.  ,330,410,415
#Sta/Elev= 14
    1000 5300.17    1050 5295.17    1140 5279.17    1200 5277.17    1240 5271.17
    1330 5271.17    1420 5270.17    1550 5270.67    1800 5270.17    1820 5271.17
    1860 5279.17    1910 5279.17    2010 5281.17    2050 5303.17
#Mann= 3 , 0 , 0
    1000    .044       0    1140    .034       0    1860    .044       0
#Block Obstruct= 2 , 0
            1100
Bank Sta=1140,1860
Sediment Elevation=0
Exp/Cntr=0.3,0.1

Type RM Length L Ch R = 1 ,20695.  ,450,450,460
#Sta/Elev= 15
    1000 5301.17    1140 5271.17    1150 5269.17    1300 5267.17    1380 5267.17
    1520 5268.17    1570 5267.17    1590 5263.17    1670 5261.17    1740 5261.17
    1780 5263.17    1790 5265.17    1880 5267.17    1970 5287.17    2160 5297.17
#Mann= 3 , 0 , 0
    1000    .044       0    1150    .034       0    1880    .044       0
Bank Sta=1150,1880
Exp/Cntr=0.3,0.1

Type RM Length L Ch R = 1 ,20245.  ,400,400,390
#Sta/Elev= 17
    1000 5299.67    1160 5267.17    1180 5265.17    1220 5263.17    1330 5261.17
    1360 5257.17    1540 5257.17    1570 5261.17    1610 5261.17    1670 5257.17
    1750 5257.17    1810 5261.17    1830 5263.17    1890 5265.17    2020 5277.17
    2070 5277.17    2250 5291.17
#Mann= 3 , 0 , 0
    1000    .044       0    1160    .034       0    1890    .044       0
Bank Sta=1160,1890
Exp/Cntr=0.3,0.1

Type RM Length L Ch R = 1 ,19845.  ,0,0,0
#Sta/Elev= 14
     980  5284.7    1000 5283.17    1041 5281.17    1082 5279.17    1134 5263.17
    1151 5259.17    1287 5259.17    1310 5261.17    1316 5263.17    1371 5279.17
    1400 5281.17    1418 5283.17    1422 5284.17    1442 5289.17
#Mann= 3 , 0 , 0
     980    .044       0    1082    .034       0    1371    .044       0
#Block Obstruct= 2 , 0
       0    1000    5290 1421.54       0    5290
Bank Sta=1082,1371
Exp/Cntr=0.3,0.1
Stream Node=Calabacillas    ,N Branch        , 0 , 0 ,Upstream end
Stream Node=Calabacillas    ,N Branch        , 0 , 1 ,Downstream end

Chan Stop Cuts=-1
Use User Specified Reach Order=0
User Specified Reach Order=Calabacillas    ,N Branch

--- NBCalab.g04 (geometry) ---

Geom Title=Revised Design Cond at Eq Slope, VD29
Program Version=3.12

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
River Reach=Calabacillas    ,N Branch

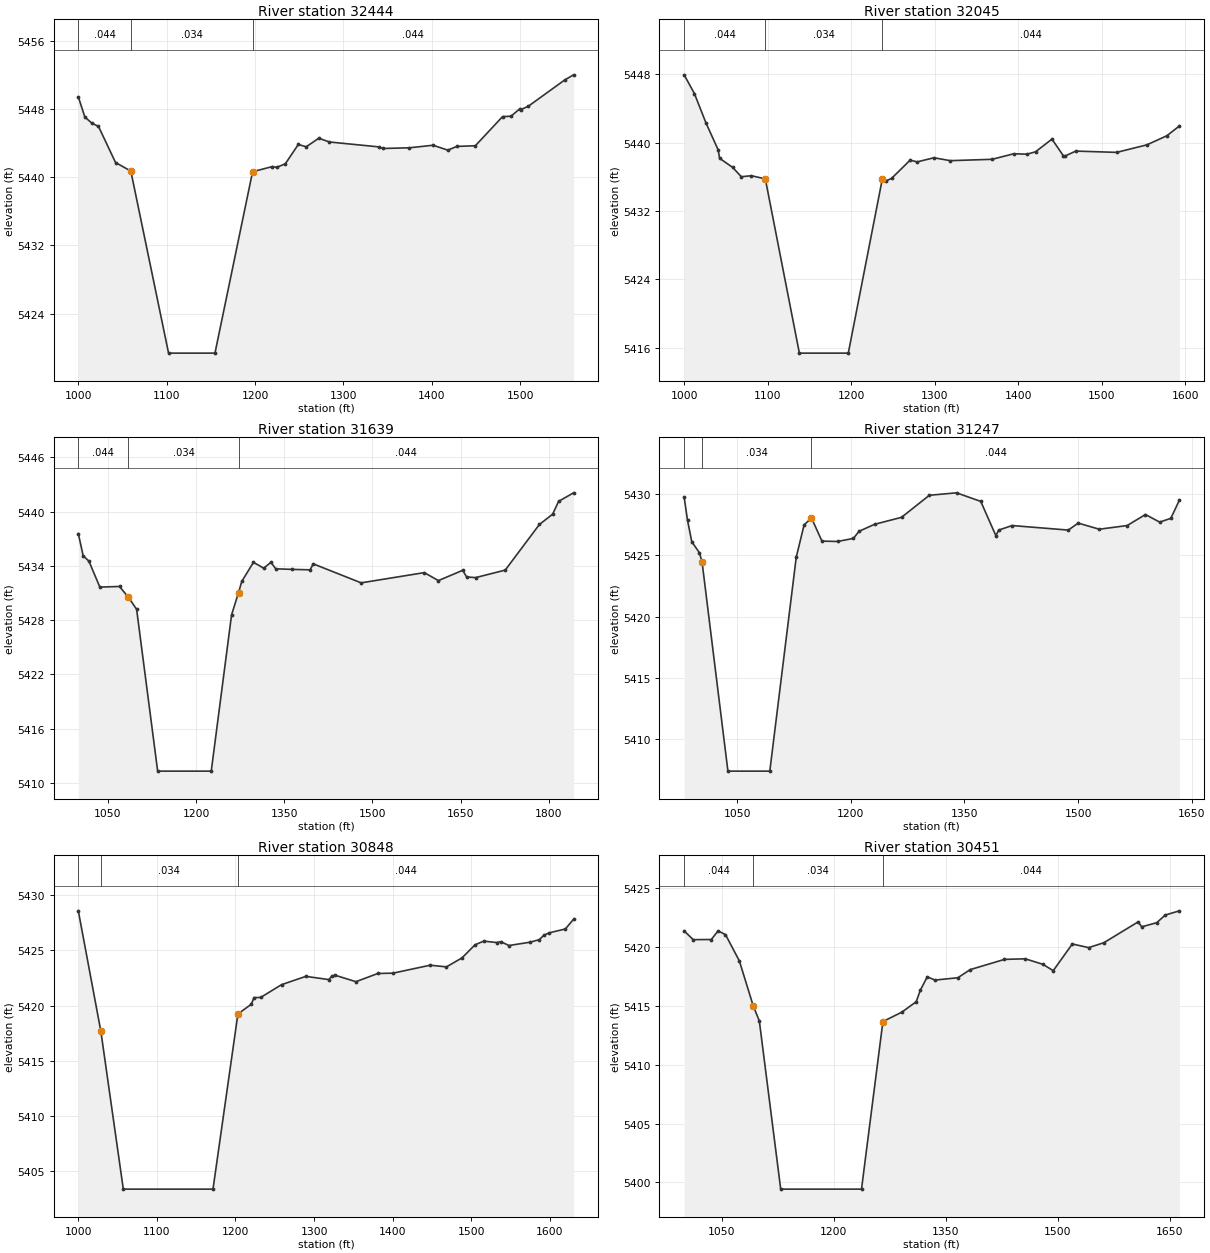
Type RM Length L Ch R = 1 ,32444   ,400,399,380
#Sta/Elev= 30
    1000 5449.43 1007.45 5447.05 1015.52 5446.33 1022.83 5445.96 1042.15 5441.72
 1059.44 5440.72 1102.16 5419.36 1154.68 5419.36 1197.24 5440.64 1219.74 5441.25
 1224.36 5441.15 1234.31 5441.57 1248.99 5443.84 1257.98 5443.57 1272.16 5444.57
 1284.27 5444.13 1339.79 5443.56 1344.85 5443.37 1374.77 5443.45 1401.51 5443.75
 1418.27 5443.17 1428.33 5443.61 1449.37 5443.69 1480.18 5447.11 1489.67 5447.15
 1499.85 5448.04 1501.25 5447.94 1509.51 5448.34 1550.42  5451.4 1560.54 5452.01
#Mann= 3 , 0 , 0
    1000    .044       0 1059.44    .034       0 1197.24    .044       0
Bank Sta=1059.44,1197.24
Sediment Elevation=0
Exp/Cntr=0.3,0.1

Type RM Length L Ch R = 1 ,32045   ,410,406,380
#Sta/Elev= 30
    1000 5447.92 1012.37 5445.71 1025.96 5442.33 1040.82 5439.12  1042.4 5438.16
 1058.09 5437.09 1068.47    5436 1080.43 5436.12 1097.18 5435.75 1137.94 5415.37
 1196.51 5415.37 1237.19 5435.71 1241.39  5435.5 1248.34 5435.81 1270.55 5437.94
 1278.99 5437.74 1299.09 5438.22 1318.55 5437.88 1368.71 5438.04 1394.61 5438.69
 1410.55 5438.64  1420.7 5438.92 1440.32  5440.4 1453.79 5438.48 1456.06 5438.43
  1468.9    5439 1517.81 5438.85 1553.95 5439.73 1577.84 5440.79 1592.92 5441.94
#Mann= 3 , 0 , 0
    1000    .044       0 1097.18    .034       0 1237.19    .044       0
Bank Sta=1097.18,1237.19
Sediment Elevation=0
Exp/Cntr=0.3,0.1

Type RM Length L Ch R = 1 ,31639   ,390,392,410
#Sta/Elev= 30
    1000 5437.56 1008.28 5435.12 1018.11 5434.51 1036.62 5431.65 1070.03 5431.72
 1085.31 5430.51 1099.13  5429.2 1134.91 5411.31 1225.99 5411.31 1260.53 5428.58
 1272.39 5431.05 1277.92 5432.28 1297.75 5434.39 1315.17 5433.74 1327.43 5434.39
 1335.67 5433.67 1363.28 5433.61 1394.07 5433.56 1399.37 5434.22 1480.79 5432.12
 1588.09 5433.25 1612.18 5432.37 1653.53 5433.51 1660.04 5432.77 1675.39  5432.7
 1725.73 5433.53 1783.78 5438.57 1806.31 5439.71 1816.47 5441.13 1841.89 5442.07
#Mann= 3 , 0 , 0
    1000    .044       0 1085.31    .034       0 1272.39    .044       0
Bank Sta=1085.31,1272.39
Sediment Elevation=0
Exp/Cntr=0.3,0.1

Type RM Length L Ch R = 1 ,31247   ,420,399,330
#Sta/Elev= 30
     980 5429.74  984.44 5427.86  990.07 5426.11 1000.18 5425.21 1003.68 5424.44
 1037.78 5407.39 1093.08 5407.39    1128 5424.85 1138.36 5427.48 1148.09 5428.05
 1161.93 5426.16 1182.55 5426.13 1203.42 5426.38 1210.89 5426.96 1231.35 5427.53
 1266.97  5428.1  1303.7  5429.9 1339.62  5430.1  1371.6  5429.4 1391.58  5426.6
 1395.27 5427.06 1412.99 5427.43 1487.15 5427.06 1500.22 5427.63 1528.04 5427.13
  1564.9 5427.43 1589.02 5428.33 1607.83 5427.71 1622.54 5428.02 1633.87 5429.51
#Mann= 3 , 0 , 0
     980    .044       0 1003.68    .034       0 1148.09    .044       0
#Block Obstruct= 2 , 0
                         1654.63
Bank Sta=1003.68,1148.09
Sediment Elevation=0
Exp/Cntr=0.3,0.1

Type RM Length L Ch R = 1 ,30848   ,400,397,400
#Sta/Elev= 30
    1000 5428.58 1028.73 5417.67 1057.27  5403.4  1171.4  5403.4  1203.1 5419.25
 1219.99 5420.12 1223.64 5420.73 1231.97 5420.74 1258.66  5421.9 1289.55 5422.65
 1318.71 5422.36 1322.61 5422.67 1326.38 5422.76 1353.32 5422.17 1381.11 5422.91
 1400.37 5422.94 1447.77 5423.66  1468.5 5423.51 1488.22 5424.32 1504.76  5425.5
 1515.86 5425.84 1532.42 5425.71 1537.76 5425.79 1547.93 5425.44  1574.7 5425.74
 1586.51 5425.97 1592.61 5426.38 1599.36 5426.59 1619.81 5426.94 1630.23 5427.82
#Mann= 3 , 0 , 0
    1000    .044       0 1028.73    .034       0  1203.1    .044       0
Bank Sta=1028.73,1203.1
Sediment Elevation=0
Exp/Cntr=0.3,0.1

Type RM Length L Ch R = 1 ,30451   ,380,392,450
#Sta/Elev= 30
    1000 5421.39 1012.11 5420.65 1036.37 5420.66  1045.3 5421.39 1055.32 5421.08
 1073.88 5418.84 1092.56 5414.99 1100.58 5413.74  1129.2 5399.43 1237.32 5399.43
 1265.95 5413.68 1291.47 5414.49 1310.53 5415.37 1316.04 5416.35 1325.35 5417.49
 1335.62 5417.21 1366.23 5417.41 1382.75  5418.1 1428.63 5418.97 1456.38 5419.02
 1480.05 5418.55 1493.88 5418.01 1519.37 5420.28 1541.31 5419.97 1561.69 5420.39
  1607.5 5422.16 1612.25 5421.74 1632.38 5422.09  1643.7 5422.74 1662.72  5423.1
#Mann= 3 , 0 , 0
    1000    .044       0 1092.56    .034       0 1265.95    .044       0
Bank Sta=1092.56,1265.95
Sediment Elevation=0
Exp/Cntr=0.3,0.1