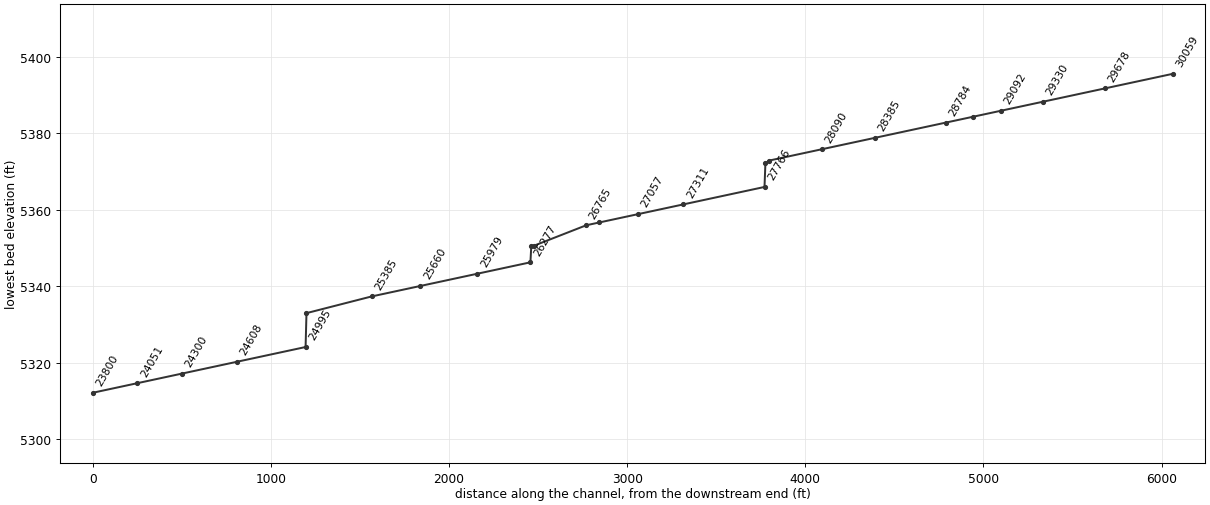
HEC-RAS study NBCalab.prj: North Branch Calabacillas Arroyo

--- NBCalab.g04 (geometry) --- (continued)

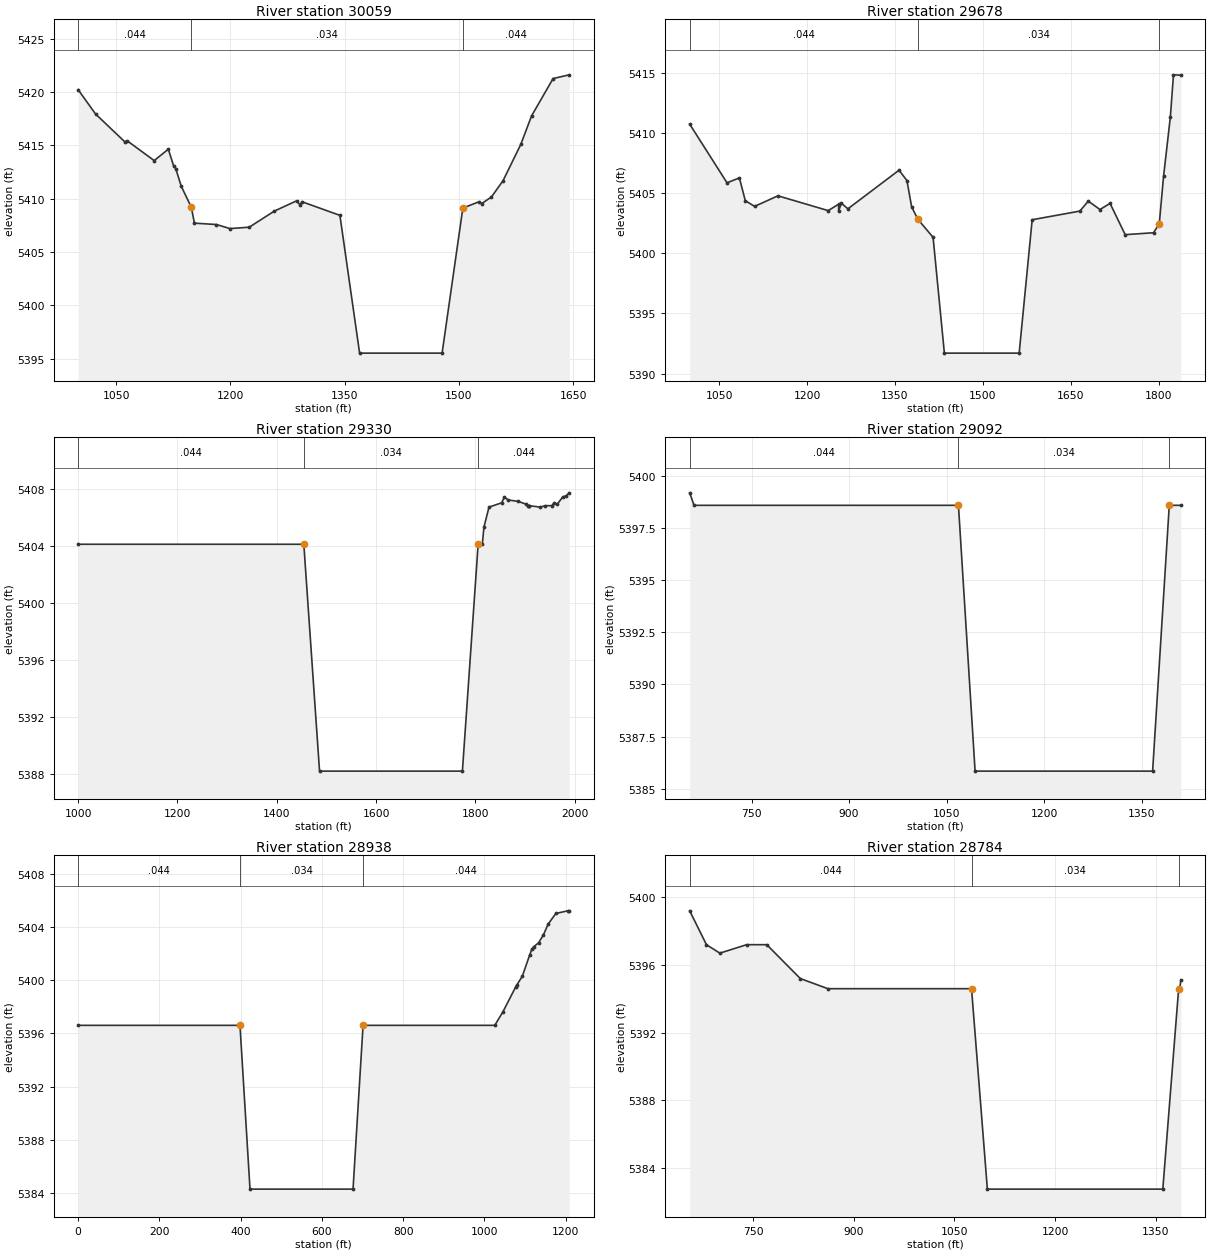
Type RM Length L Ch R = 1 ,30059   ,400,381,350
#Sta/Elev= 30
    1000 5420.24 1022.85 5417.96  1061.2 5415.35  1064.6 5415.43 1099.92 5413.58
 1118.43 5414.65 1125.44 5413.08 1128.19 5412.83 1135.38 5411.18 1148.64  5409.2
  1152.7 5407.71 1181.61 5407.58 1199.38  5407.2  1224.7 5407.33 1257.61 5408.84
 1286.74  5409.8 1291.61 5409.41 1293.89 5409.72 1343.71 5408.44 1369.57 5395.51
 1477.87 5395.51 1505.09 5409.12 1526.04 5409.71 1529.85 5409.55 1542.56 5410.16
 1557.83 5411.69 1581.17  5415.1 1595.35 5417.78 1623.57 5421.28 1644.81 5421.63
#Mann= 3 , 0 , 0
    1000    .044       0 1148.64    .034       0 1505.09    .044       0
Bank Sta=1148.64,1505.09
Sediment Elevation=0
Exp/Cntr=0.3,0.1

Type RM Length L Ch R = 1 ,29678   ,289,348,311
BEGIN DESCRIPTION:
Existing Section
END DESCRIPTION:
#Sta/Elev= 30
    1000 5410.74 1063.65 5405.86  1084.7 5406.27 1094.76 5404.38 1110.69  5403.9
 1150.45 5404.78  1236.1 5403.55 1253.89 5404.08  1253.9 5403.53 1258.69 5404.16
 1269.72  5403.7 1356.88 5406.91 1370.34 5406.05 1378.38 5403.86 1388.96 5402.83
 1414.91 5401.33 1434.17  5391.7 1561.66  5391.7 1583.84 5402.79 1665.14 5403.51
 1679.54 5404.34 1699.36 5403.64  1716.6 5404.15  1742.4 5401.55  1790.7 5401.71
  1800.5 5402.45  1807.8  5406.4  1819.4 5411.33  1824.7 5414.84  1837.3 5414.81
#Mann= 3 , 0 , 0
    1000    .044       0 1388.96    .034       0  1800.5    .044       0
#Block Obstruct= 2 , 0
         1357.19
Bank Sta=1388.96,1800.5
Sediment Elevation=0
Exp/Cntr=0.3,0.1

Type RM Length L Ch R = 1 ,29330   ,238,238,238
BEGIN DESCRIPTION:
Spur 10L
END DESCRIPTION:
#Sta/Elev= 24
    1000  5404.1  1454.5  5404.1 1486.17 5388.22 1773.83 5388.22  1805.5  5404.1
  1813.9  5404.1  1817.2  5405.3  1827.4  5406.7  1852.8    5407  1858.4  5407.4
  1866.1  5407.2  1886.3  5407.1  1902.5  5406.9  1906.9  5406.8  1907.2  5406.8
  1908.3  5406.8  1930.3  5406.7  1941.1  5406.8  1953.8  5406.8  1958.8    5407
  1964.9  5406.9  1975.5  5407.4  1983.2  5407.5    1989  5407.7
#Mann= 3 , 0 , 0
    1000    .044       0  1454.5    .034       0  1805.5    .044       0
#Block Obstruct= 2 , 0
         1140.51
Bank Sta=1454.5,1805.5
Sediment Elevation=0
Exp/Cntr=0.3,0.1

Type RM Length L Ch R = 1 ,29092   ,154,154,154
BEGIN DESCRIPTION:
Spur 10R
END DESCRIPTION:
#Sta/Elev= 7
     655  5399.2   661.7  5398.6    1068  5398.6 1093.59 5385.84 1366.41 5385.84
    1392  5398.6  1409.8  5398.6
#Mann= 3 , 0 , 0
     655    .044       0    1068    .034       0    1392    .044       0
Bank Sta=1068,1392
Sediment Elevation=0
Exp/Cntr=0.3,0.1

Type RM Length L Ch R = 1 ,28938   ,154,154,154
BEGIN DESCRIPTION:
Spur 9L
END DESCRIPTION:
#Sta/Elev= 19
       0  5396.6   398.5  5396.6  423.18  5384.3  676.82  5384.3   701.5  5396.6
  1025.8  5396.6  1045.5  5397.6  1077.5  5399.5  1079.5  5399.6  1093.7  5400.3
  1111.8  5401.9  1116.8  5402.3  1121.6  5402.5  1133.6  5402.8  1145.6  5403.4
    1157  5404.2    1176    5405  1205.1  5405.2  1209.1  5405.2
#Mann= 3 , 0 , 0
       0    .044       0   398.5    .034       0   701.5    .044       0
#Block Obstruct= 2 , 0
                          1386.4
Bank Sta=398.5,701.5
Sediment Elevation=0
Exp/Cntr=0.3,0.1

Type RM Length L Ch R = 1 ,28784   ,399,399,399
BEGIN DESCRIPTION:
Spur9R
END DESCRIPTION:
#Sta/Elev= 13
     655  5399.2     680  5397.2     700  5396.7     740  5397.2     770  5397.2
     820  5395.2   861.2  5394.6  1075.5  5394.6 1099.12 5382.76 1360.88 5382.76
  1384.5  5394.6  1386.1  5394.6  1387.8  5395.1
#Mann= 3 , 0 , 0
     655    .044       0  1075.5    .034       0  1384.5    .044       0
#Block Obstruct= 2 , 0
                          1386.4
Bank Sta=1075.5,1384.5
Sediment Elevation=0
Exp/Cntr=0.3,0.1

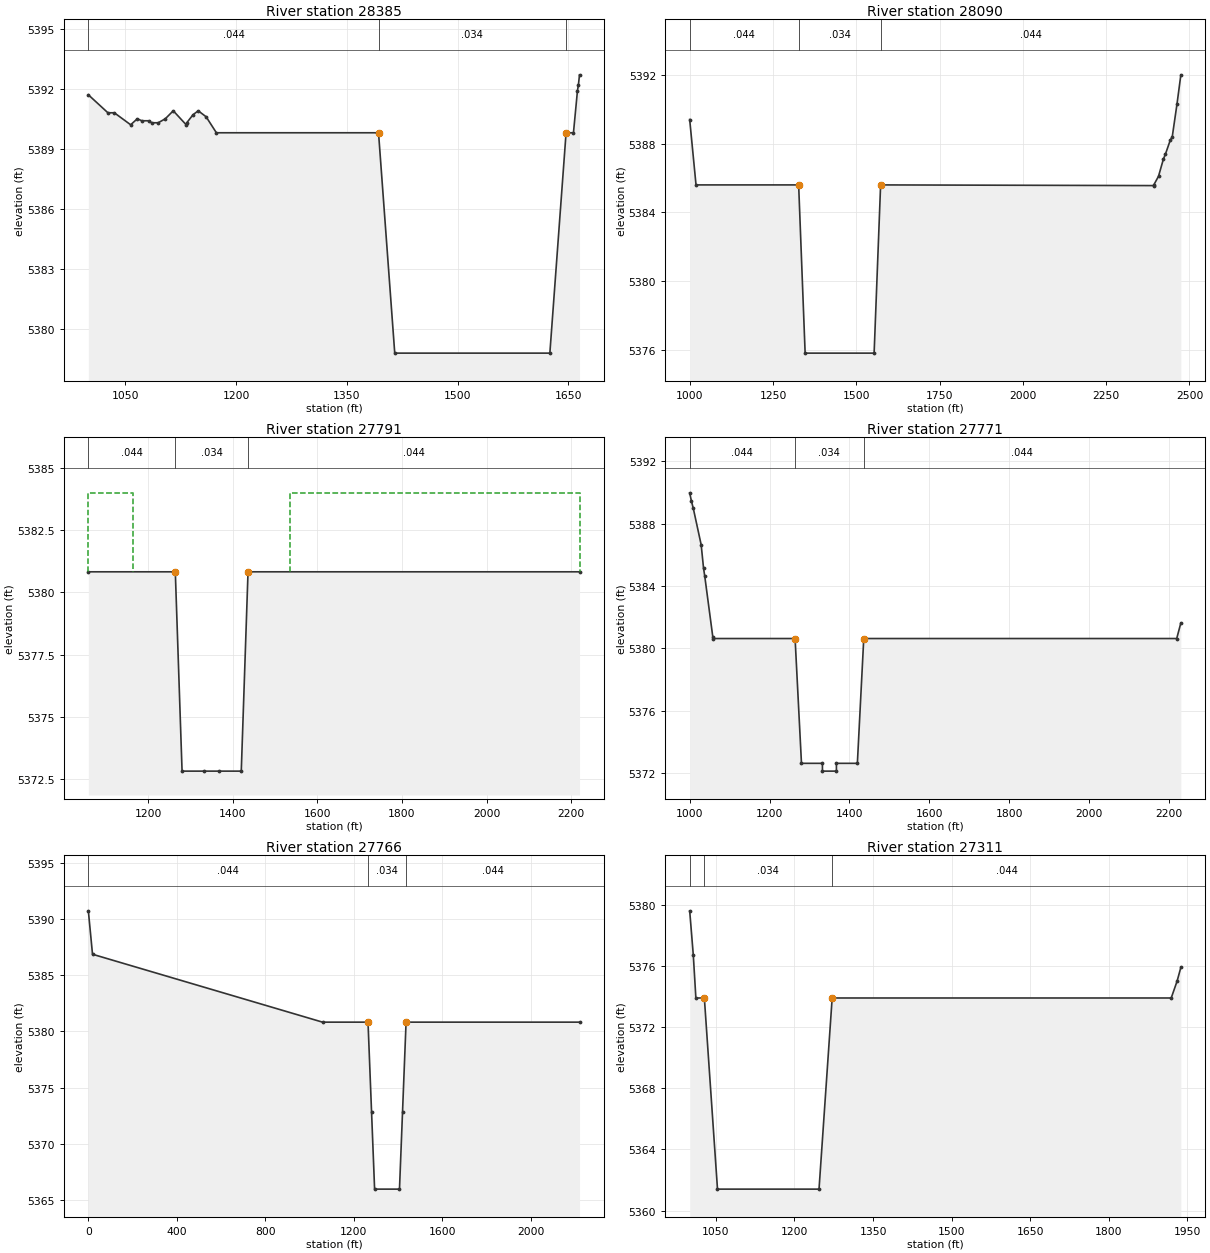
Type RM Length L Ch R = 1 ,28385   ,285,295,310
BEGIN DESCRIPTION:
Spur 8L,R
END DESCRIPTION:
#Sta/Elev= 25
    1000  5391.7  1026.5  5390.8  1035.2  5390.8  1057.3  5390.2  1066.3  5390.5
  1072.4  5390.4  1082.7  5390.4  1085.6  5390.3  1094.6  5390.3  1104.2  5390.5
    1115  5390.9  1132.5  5390.2  1133.3  5390.3  1141.7  5390.7  1148.8  5390.9
  1159.5  5390.6  1173.4  5389.8    1393  5389.8 1414.96 5378.77 1625.04 5378.77
    1647  5389.8    1657  5389.8  1662.4  5391.9  1663.7  5392.2  1665.2  5392.7
#Mann= 3 , 0 , 0
    1000    .044       0    1393    .034       0    1647    .044       0
Bank Sta=1393,1647
Sediment Elevation=0
Exp/Cntr=0.3,0.1

Type RM Length L Ch R = 1 ,28090   ,299,299,299
BEGIN DESCRIPTION:
Spur 7L
END DESCRIPTION:
#Sta/Elev= 15
    1000  5389.4    1019  5385.6    1327  5385.6 1346.48 5375.82 1553.52 5375.82
    1573  5385.6 2392.01 5385.56 2392.04 5385.57    2407  5386.1  2421.7  5387.1
    2428  5387.4  2442.3  5388.2  2448.3  5388.4  2462.5  5390.3  2474.1    5392
#Mann= 3 , 0 , 0
    1000    .044       0    1327    .034       0    1573    .044       0
#Block Obstruct= 2 , 0
                            1600
Bank Sta=1327,1573
Sediment Elevation=0
Exp/Cntr=0.3,0.1

Type RM Length L Ch R = 1 ,27791   ,20,20,20
BEGIN DESCRIPTION:
GCS4 Inlet Section
END DESCRIPTION:
#Sta/Elev= 8
 1058.37 5380.83    1264 5380.83    1280 5372.83  1332.5 5372.83  1367.5 5372.83
    1420 5372.83    1436 5380.83 2219.91 5380.83
#Mann= 3 , 0 , 0
 1058.37    .044       0    1264    .034       0    1436    .044       0
#XS Ineff= 2 , 0
       0    1164    5384    1536       0    5384
Permanent Ineff=
       F       F
Bank Sta=1264,1436
Sediment Elevation=0
Exp/Cntr=0.3,0.1

Type RM Length L Ch R = 1 ,27771   ,5,5,5
BEGIN DESCRIPTION:
GCS4 Crest
END DESCRIPTION:
#Sta/Elev= 18
    1000 5389.97 1004.07 5389.47 1009.06 5388.97 1028.76 5386.64 1034.74 5385.13
 1037.66 5384.64 1057.96 5380.72 1058.37 5380.63    1264 5380.63    1280 5372.63
  1332.5 5372.63  1332.5 5372.13  1367.5 5372.13  1367.5 5372.63    1420 5372.63
    1436 5380.63 2219.91 5380.63 2230.28 5381.63
#Mann= 3 , 0 , 0
    1000    .044       0    1264    .034       0    1436    .044       0
Bank Sta=1264,1436
Sediment Elevation=0
Exp/Cntr=0.3,0.1

Type RM Length L Ch R = 1 ,27766   ,525,455,425
BEGIN DESCRIPTION:
GCS4 Base (below drop, idealized to EQS)
END DESCRIPTION:
#Sta/Elev= 10
       0 5390.75   18.82 5386.88 1058.37 5380.83    1264 5380.83    1280 5372.83
 1293.76 5365.95 1406.24 5365.95    1420 5372.83    1436 5380.83 2219.91 5380.83
#Mann= 3 , 0 , 0
       0    .044       0    1264    .034       0    1436    .044       0
Bank Sta=1264,1436
Sediment Elevation=0
Exp/Cntr=0.3,0.1

Type RM Length L Ch R = 1 ,27311   ,254,254,254
BEGIN DESCRIPTION:
Spur6L
END DESCRIPTION:
#Sta/Elev= 10
    1000  5379.6  1006.9  5376.7  1011.8  5373.9    1028  5373.9 1053.08  5361.4
 1246.92  5361.4    1272  5373.9  1919.3  5373.9  1930.5    5375  1937.7  5375.9
#Mann= 3 , 0 , 0
    1000    .044       0    1028    .034       0    1272    .044       0
Bank Sta=1028,1272
Sediment Elevation=0
Exp/Cntr=0.3,0.1

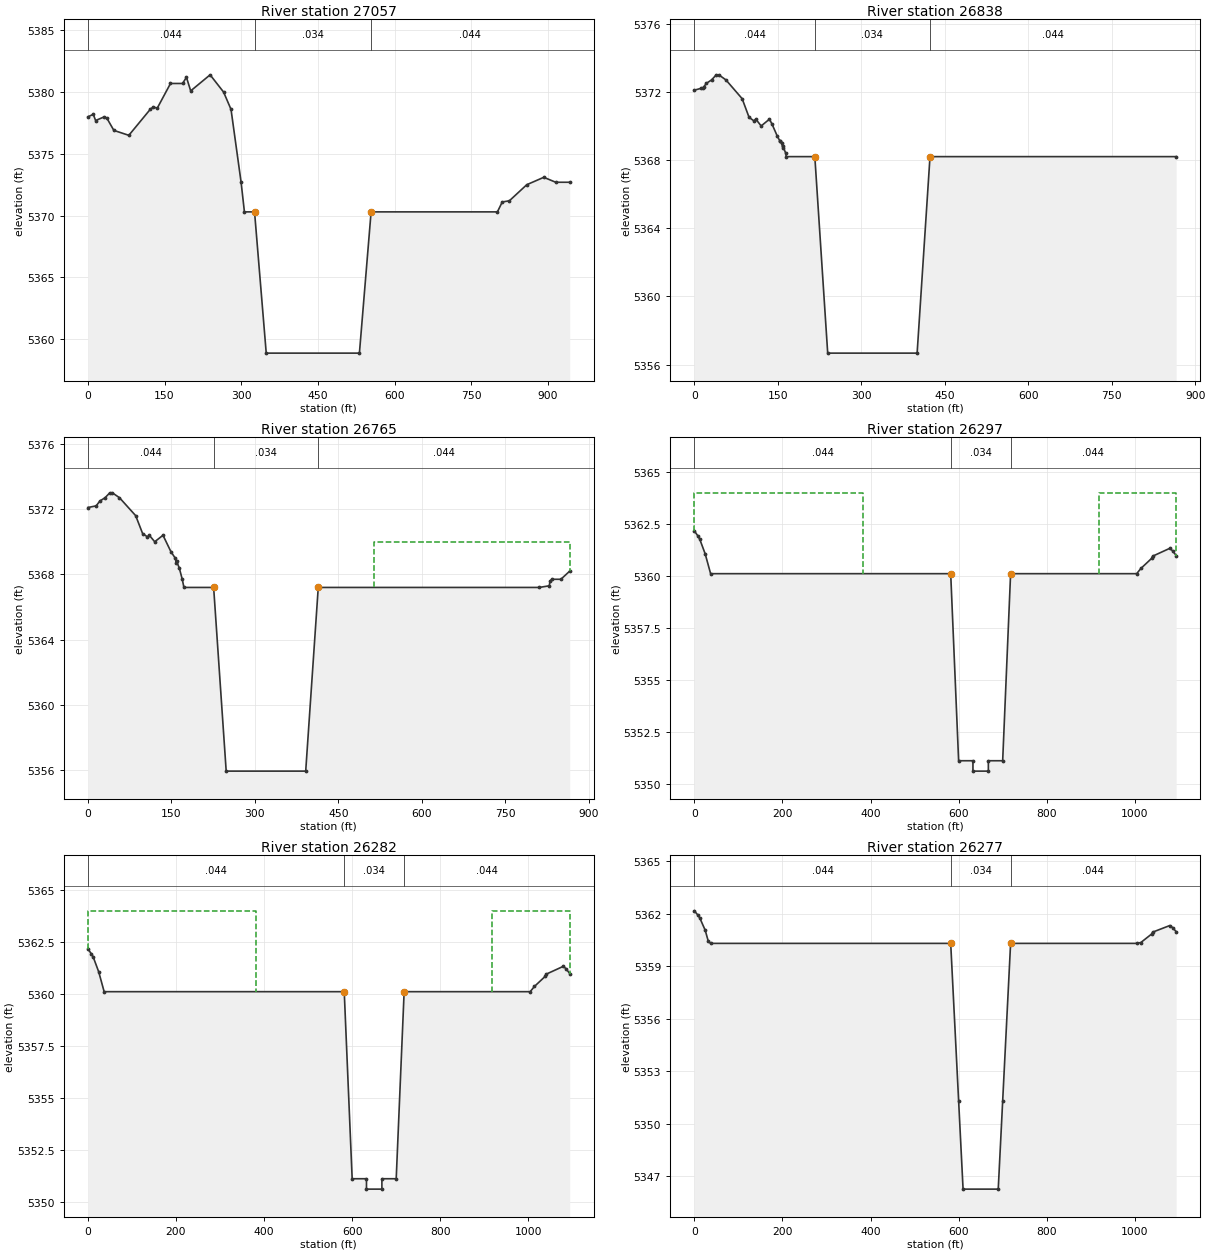
Type RM Length L Ch R = 1 ,27057   ,219,219,219
BEGIN DESCRIPTION:
Spur 5L,R
END DESCRIPTION:
#Sta/Elev= 30
       0    5378    10.6  5378.2    15.1  5377.7    32.2    5378      37  5377.9
    50.8  5376.9    80.1  5376.5   121.9  5378.6     128  5378.8   135.7  5378.7
   161.6  5380.7   185.2  5380.7   192.8  5381.2   201.1  5380.1   239.1  5381.4
   265.5    5380     280  5378.6   299.7  5372.7   306.2  5370.3     326  5370.3
  348.86 5358.86  531.14 5358.86     554  5370.3   801.1  5370.3   810.5  5371.1
   824.5  5371.2   858.5  5372.5   891.8  5373.1   915.1  5372.7   942.5  5372.7
#Mann= 3 , 0 , 0
       0    .044       0     326    .034       0     554    .044       0
Bank Sta=326,554
Sediment Elevation=0
Exp/Cntr=0.3,0.1

Type RM Length L Ch R = 1 ,26838   ,73,73,73
BEGIN DESCRIPTION:
Spur4R
END DESCRIPTION:
#Sta/Elev= 29
       0  5372.1    11.2  5372.2    14.9  5372.2    17.1  5372.3    21.6  5372.5
    30.9  5372.7    39.4    5373      44    5373    56.8  5372.7    85.9  5371.6
    98.4  5370.5   107.1  5370.3   110.4  5370.4   120.1    5370     135  5370.4
   139.7  5370.1   149.1  5369.4     154  5369.1   154.3  5369.1   156.9    5369
   159.1  5368.7   159.4  5368.8   164.2  5368.4   165.1  5368.2   216.5  5368.2
  239.65 5356.67  400.35 5356.67   423.5  5368.2   865.9  5368.2
#Mann= 3 , 0 , 0
       0    .044       0   216.5    .034       0   423.5    .044       0
Bank Sta=216.5,423.5
Sediment Elevation=0
Exp/Cntr=0.3,0.1

Type RM Length L Ch R = 1 ,26765   ,293,293,305
BEGIN DESCRIPTION:
Spur 4L
END DESCRIPTION:
#Sta/Elev= 30
       0  5372.1    14.9  5372.2    21.6  5372.5    30.9  5372.7    39.4    5373
      44    5373    56.8  5372.7    85.9  5371.6    98.4  5370.5   107.1  5370.3
   110.4  5370.4   120.1    5370     135  5370.4   149.1  5369.4   156.9    5369
   159.1  5368.7   159.4  5368.8   164.2  5368.4   169.6  5367.7   172.6  5367.2
     226  5367.2  248.55 5355.94  391.45 5355.94     414  5367.2     811  5367.2
   829.1  5367.3   830.7  5367.6   833.8  5367.7     850  5367.7   865.9  5368.2
#Mann= 3 , 0 , 0
       0    .044       0     226    .034       0     414    .044       0
#XS Ineff= 2 , 0
       0                     514       0    5370
Permanent Ineff=
       F       T
Bank Sta=226,414
Exp/Cntr=0.3,0.1

Type RM Length L Ch R = 1 ,26297   ,15,15,15
BEGIN DESCRIPTION:
GCS3 U/S Sill (Flat across sill)
END DESCRIPTION:
#Sta/Elev= 20
       0 5362.17     8.2 5361.92   12.23 5361.77   24.66 5361.06   36.91 5360.11
     582 5360.11     600 5351.11   632.5 5351.11   632.5 5350.61   667.5 5350.61
   667.5 5351.11     700 5351.11     718 5360.11 1004.21 5360.11 1013.73 5360.36
 1038.91 5360.86 1040.29 5360.95 1079.44 5361.33  1085.8 5361.21 1093.91 5360.98
#Mann= 3 , 0 , 0
       0    .044       0     582    .034       0     718    .044       0
#XS Ineff= 2 , 0
       0     382    5364     918       0    5364
Permanent Ineff=
       F       F
Bank Sta=582,718
Sediment Elevation=0
Exp/Cntr=0.3,0.1

Type RM Length L Ch R = 1 ,26282   ,5,5,5
BEGIN DESCRIPTION:
GCS3 Crest
END DESCRIPTION:
#Sta/Elev= 20
       0 5362.17     8.2 5361.92   12.23 5361.77   24.66 5361.06   36.91 5360.11
     582 5360.11     600 5351.11   632.5 5351.11   632.5 5350.61   667.5 5350.61
   667.5 5351.11     700 5351.11     718 5360.11 1004.21 5360.11 1013.73 5360.36
 1038.91 5360.86 1040.29 5360.95 1079.44 5361.33  1085.8 5361.21 1093.91 5360.98
#Mann= 3 , 0 , 0
       0    .044       0     582    .034       0     718    .044       0
#XS Ineff= 2 , 0
       0     382    5364     918       0    5364
Permanent Ineff=
       T       T
Bank Sta=582,718
Sediment Elevation=0
Exp/Cntr=0.3,0.1

Type RM Length L Ch R = 1 ,26277   ,246,298,313
BEGIN DESCRIPTION:
GCS3 Base (below drop, idealized to EQS)
END DESCRIPTION:
#Sta/Elev= 19
       0 5362.17     8.2 5361.92   12.23 5361.77   24.66 5361.06   31.67 5360.43
   36.91 5360.31     582 5360.31     600 5351.31  610.08 5346.27  689.92 5346.27
     700 5351.31     718 5360.31 1004.21 5360.31 1013.73 5360.36 1038.91 5360.86
 1040.29 5360.95 1079.44 5361.33  1085.8 5361.21 1093.91 5360.98
#Mann= 3 , 0 , 0
       0    .044       0     582    .034       0     718    .044       0
Bank Sta=582,718
Sediment Elevation=0
Exp/Cntr=0.3,0.1

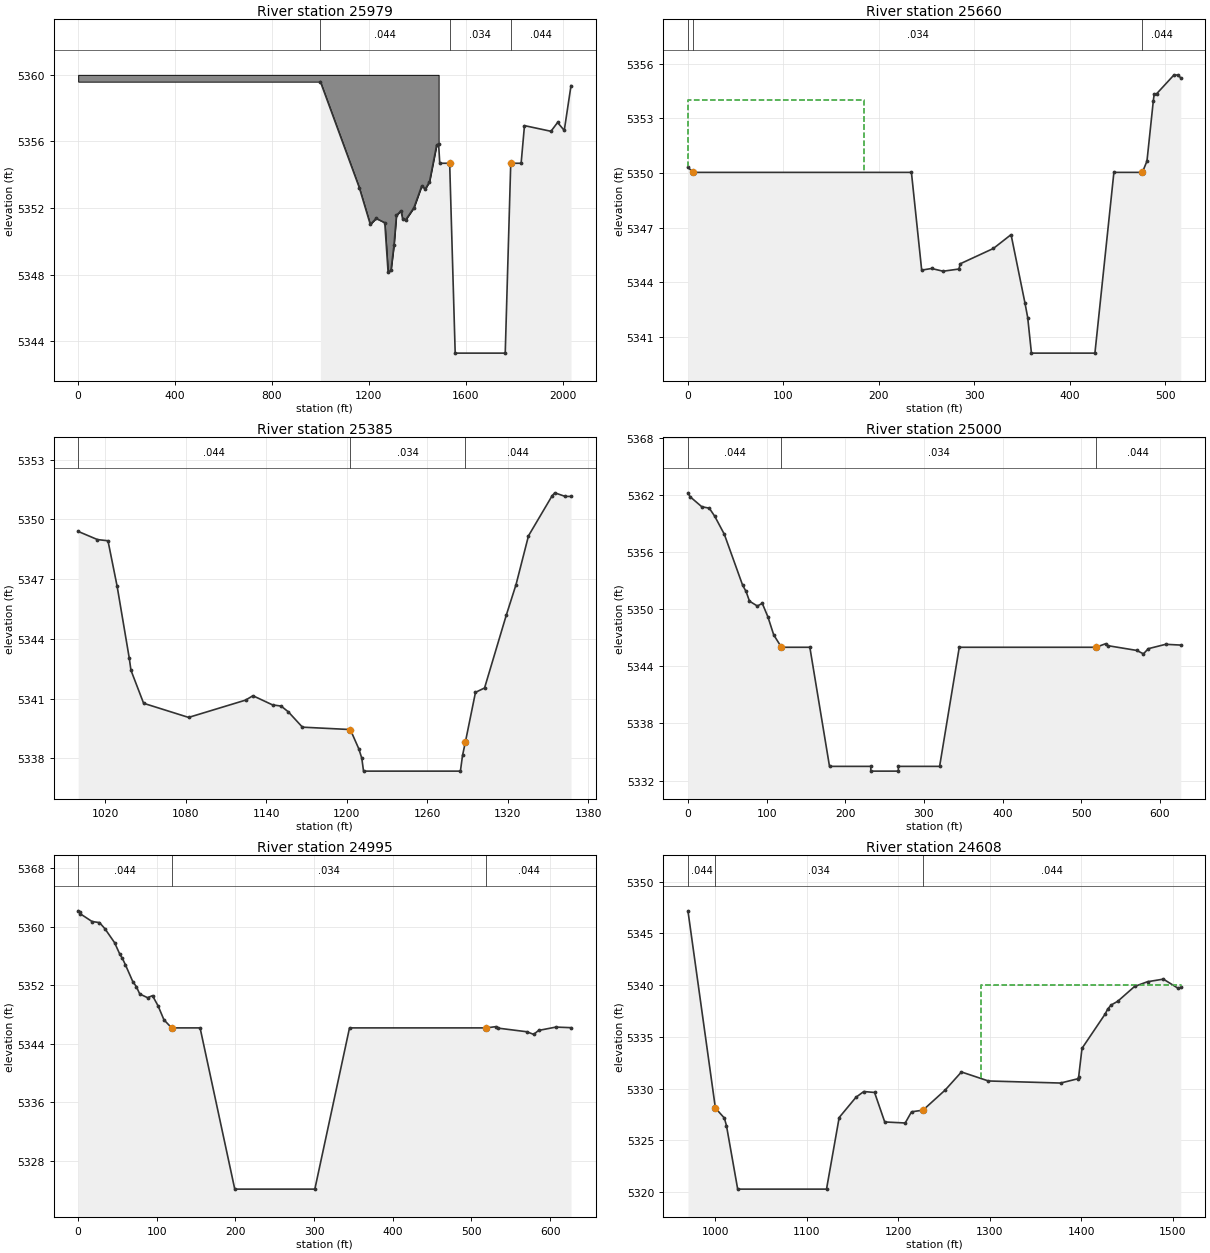
Type RM Length L Ch R = 1 ,25979   ,295,319,371
BEGIN DESCRIPTION:
Fill Section at 25979
END DESCRIPTION:
#Sta/Elev= 30
    1000 5359.59 1160.58 5353.23 1206.02 5351.02 1230.24 5351.38 1265.92 5351.12
  1279.6 5348.14  1291.4 5348.26 1303.82 5349.76 1314.05 5351.56 1332.71 5351.84
 1339.63 5351.35 1352.54  5351.3 1386.17 5352.02 1417.64  5353.3 1433.74 5353.16
 1450.47 5353.58    1480 5355.78 1488.18 5355.84 1492.88 5354.69    1534 5354.69
    1534 5354.59 1556.61 5343.29 1763.21 5343.29    1786 5354.69 1828.85 5354.69
 1842.67 5356.95 1952.08 5356.61 1979.44 5357.14 2006.92 5356.66 2034.82 5359.35
#Mann= 3 , 0 , 0
    1000    .044       0    1534    .034       0    1786    .044       0
#Block Obstruct= 2 , 0
       0 1488.18    5360               0
Bank Sta=1534,1786
Sediment Elevation=0
Exp/Cntr=0.3,0.1

Type RM Length L Ch R = 1 ,25660   ,317,275,250
BEGIN DESCRIPTION:
Spur3, rb represents d/s limit of rb riprap
END DESCRIPTION:
#Sta/Elev= 23
       0 5350.31    5.39 5350.03     234 5350.03  244.74 5344.66  255.15 5344.75
  267.14  5344.6  283.71 5344.72  285.17 5345.01  319.81 5345.85  338.33 5346.61
  352.98 5342.83  355.76 5342.05  359.66  5340.1  426.14  5340.1     446 5350.03
   475.8 5350.03  480.63 5350.65  487.26 5353.95  488.17 5354.33  490.94 5354.36
  508.49 5355.36  512.99 5355.39  516.03 5355.22
#Mann= 3 , 0 , 0
       0    .044       0    5.39    .034       0   475.8    .044       0
#XS Ineff= 2 , 0
       0     184    5354               0
Permanent Ineff=
       T       F
Bank Sta=5.39,475.8
Sediment Elevation=0
Exp/Cntr=0.3,0.1

Type RM Length L Ch R = 1 ,25385   ,417,365,335
BEGIN DESCRIPTION:
Existing Section, no fill necessary
END DESCRIPTION:
#Sta/Elev= 30
    1000  5349.4 1014.34 5348.99 1022.19 5348.93 1029.01 5346.64 1038.04 5343.03
  1039.3 5342.42 1048.73 5340.76 1082.22 5340.05 1124.66 5340.92 1130.14 5341.14
 1144.72 5340.68 1151.14 5340.62 1156.49 5340.33 1166.99 5339.56 1202.64 5339.44
 1208.92 5338.48 1211.19    5338 1212.49 5337.35 1284.63 5337.35 1286.21 5338.14
 1288.26 5338.79 1295.85 5341.31 1302.61 5341.53 1318.79 5345.19 1326.06 5346.73
 1335.33 5349.18    1353  5351.2 1354.94 5351.34 1362.63 5351.16 1366.99 5351.16
#Mann= 3 , 0 , 0
    1000    .044       0 1202.64    .034       0 1288.26    .044       0
Bank Sta=1202.64,1288.26
Sediment Elevation=0
Exp/Cntr=0.3,0.1

Type RM Length L Ch R = 1 ,25000   ,5,5,5
BEGIN DESCRIPTION:
GCS2 Crest
END DESCRIPTION:
#Sta/Elev= 30
       0 5362.21    2.61 5361.81   17.59 5360.75    27.1  5360.6   34.02 5359.76
   46.26 5357.86   69.49 5352.52   73.89 5351.86   78.26 5350.84   88.24 5350.33
   94.51 5350.61  101.64  5349.2  109.07  5347.3  118.88    5346     155    5346
     180  5333.5   232.5  5333.5   232.5    5333   267.5    5333   267.5  5333.5
     320  5333.5     345    5346  518.84    5346  530.99 5346.37  533.77 5346.17
  570.56 5345.67  579.18 5345.31  585.32 5345.85   607.4 5346.31  626.63 5346.23
#Mann= 3 , 0 , 0
       0    .044       0  118.88    .034       0  518.84    .044       0
Bank Sta=118.88,518.84
Sediment Elevation=0
Exp/Cntr=0.3,0.1

Type RM Length L Ch R = 1 ,24995   ,475,387,275
BEGIN DESCRIPTION:
GCS2 Bottom
END DESCRIPTION:
#Sta/Elev= 30
       0 5362.21    2.18 5362.02    2.61 5361.81   17.59 5360.75    27.1  5360.6
   34.02 5359.76   46.26 5357.86   53.02 5356.26   56.23  5355.7   59.97 5354.85
   69.49 5352.52   73.89 5351.86   78.26 5350.84   88.24 5350.33   94.51 5350.61
  101.64  5349.2  109.07  5347.3  118.88  5346.2     155  5346.2   199.1 5324.15
   300.9 5324.15     345  5346.2  518.84  5346.2  530.99 5346.37  533.77 5346.17
  570.56 5345.67  579.18 5345.31  585.32 5345.85   607.4 5346.31  626.63 5346.23
#Mann= 3 , 0 , 0
       0    .044       0  118.88    .034       0  518.84    .044       0
Bank Sta=118.88,518.84
Sediment Elevation=0
Exp/Cntr=0.3,0.1

Type RM Length L Ch R = 1 ,24608   ,320,308,300
BEGIN DESCRIPTION:
Cut from Goodwin (2003) Mapping
END DESCRIPTION:
#Sta/Elev= 30
     970 5347.17    1000 5328.11 1009.78 5327.15 1012.09 5326.42 1024.37 5320.28
 1121.44 5320.28 1135.28  5327.2 1153.68 5329.16 1162.17 5329.71 1173.95 5329.62
 1185.06 5326.77 1207.44 5326.67 1214.35 5327.75 1226.84 5327.91 1251.08 5329.85
 1268.89  5331.6  1298.4 5330.73 1377.25 5330.53 1396.35 5330.95 1397.01 5331.13
 1400.64 5333.88 1426.03 5337.21 1428.66 5337.67 1432.52 5338.07 1439.71 5338.43
 1458.07 5339.86 1472.24 5340.32  1489.6 5340.57 1505.61 5339.69  1508.6 5339.77
#Mann= 3 , 0 , 0
     970    .044       0    1000    .034       0 1226.84    .044       0
#XS Ineff= 2 , 0
       0                    1290       0    5340
Permanent Ineff=
       F       T
Bank Sta=1000,1226.84
Exp/Cntr=0.3,0.1

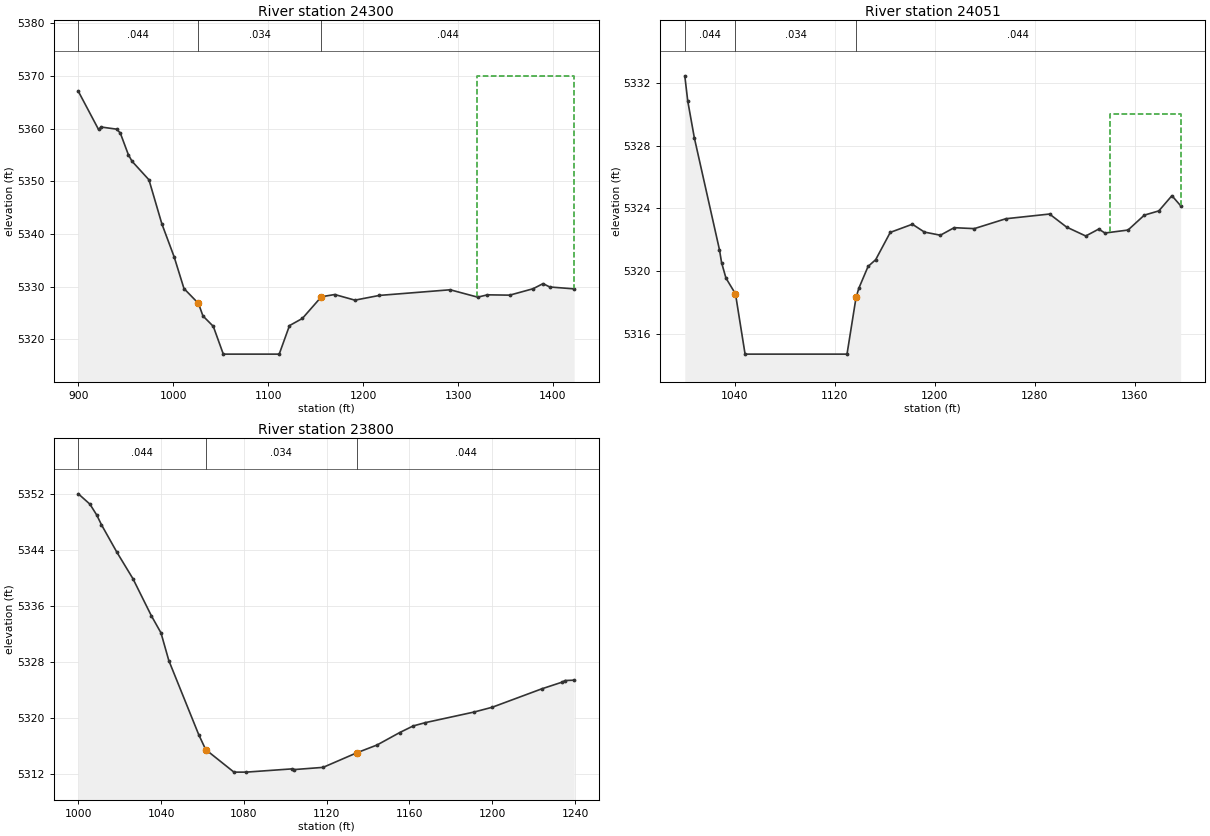
Type RM Length L Ch R = 1 ,24300   ,388,249,160
BEGIN DESCRIPTION:
Spur2 - removed per Dan's email on 2/10/05
END DESCRIPTION:
#Sta/Elev= 30
     900 5367.06  921.26 5359.83  924.25 5360.28  940.37 5359.88   944.2 5359.15
  952.65 5355.06  956.52  5353.8   974.4 5350.27  987.98 5341.92 1000.94 5335.65
 1011.28 5329.64 1026.57 5326.81 1031.25 5324.45 1042.17 5322.47 1052.71  5317.2
  1111.6  5317.2 1122.42 5322.61 1135.99 5323.97 1156.03 5328.08 1170.08 5328.51
 1191.35 5327.44 1217.19 5328.34 1291.71 5329.41 1320.65 5328.01 1330.99 5328.45
 1354.46 5328.39 1379.09 5329.61 1389.55 5330.58 1396.52 5329.94  1422.3 5329.58
#Mann= 3 , 0 , 0
     900    .044       0 1026.57    .034       0 1156.03    .044       0
#XS Ineff= 2 , 0
       0                    1320       0    5370
Permanent Ineff=
       F       T
Bank Sta=1026.57,1156.03
Sediment Elevation=0
Exp/Cntr=0.3,0.1

Type RM Length L Ch R = 1 ,24051   ,350,251,150
BEGIN DESCRIPTION:
From BHI (2000) Mapping, adjusted to VD29
END DESCRIPTION:
#Sta/Elev= 30
    1000 5332.45 1002.34 5330.85 1007.65 5328.49 1027.71 5321.37  1029.4 5320.55
  1032.9 5319.56 1040.53 5318.55 1048.21 5314.71 1129.73 5314.71 1136.95 5318.32
 1139.18 5318.91 1146.57  5320.3 1152.65 5320.73  1164.3 5322.47 1181.98 5322.99
 1191.63 5322.49 1204.39 5322.29 1215.41 5322.77 1231.51 5322.71 1256.71 5323.34
 1291.71 5323.64  1305.3 5322.81 1320.65 5322.24 1330.99 5322.68 1336.02 5322.43
 1354.46 5322.62 1367.49 5323.57 1379.09 5323.84 1389.55 5324.81 1396.52 5324.17
#Mann= 3 , 0 , 0
    1000    .044       0 1040.53    .034       0 1136.95    .044       0
#XS Ineff= 2 , 0
       0                    1340       0    5330
Permanent Ineff=
       F       T
Bank Sta=1040.53,1136.95
Exp/Cntr=0.3,0.1

Type RM Length L Ch R = 1 ,23800   ,351,150,151
BEGIN DESCRIPTION:
Existing Section 23800, U/S limit of caliche (no incision) Caliche
END DESCRIPTION:
#Sta/Elev= 27
    1000 5351.97 1005.61 5350.49 1008.87 5348.95 1011.18 5347.55 1018.66 5343.61
 1026.41 5339.83 1035.23 5334.58 1039.94  5332.1 1043.72 5328.15 1058.17 5317.56
 1061.55 5315.42  1075.2  5312.2 1081.15  5312.2 1103.06 5312.66 1104.05 5312.56
 1118.27 5312.88 1134.54 5314.96 1144.37 5316.08 1155.33 5317.86 1161.82  5318.8
 1167.65 5319.27 1191.27 5320.79 1199.99 5321.47 1223.92  5324.1 1233.69 5325.05
 1235.24 5325.29  1239.6 5325.34
#Mann= 3 , 0 , 0
    1000    .044       0 1061.55    .034       0 1134.54    .044       0
Bank Sta=1061.55,1134.54
Sediment Elevation=0
Exp/Cntr=0.3,0.1

--- NBCalab.g05 (geometry) ---

Geom Title=Revised Design Cond at Ex Grd, Reduced n
Program Version=3.12

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
River Reach=Calabacillas    ,N Branch

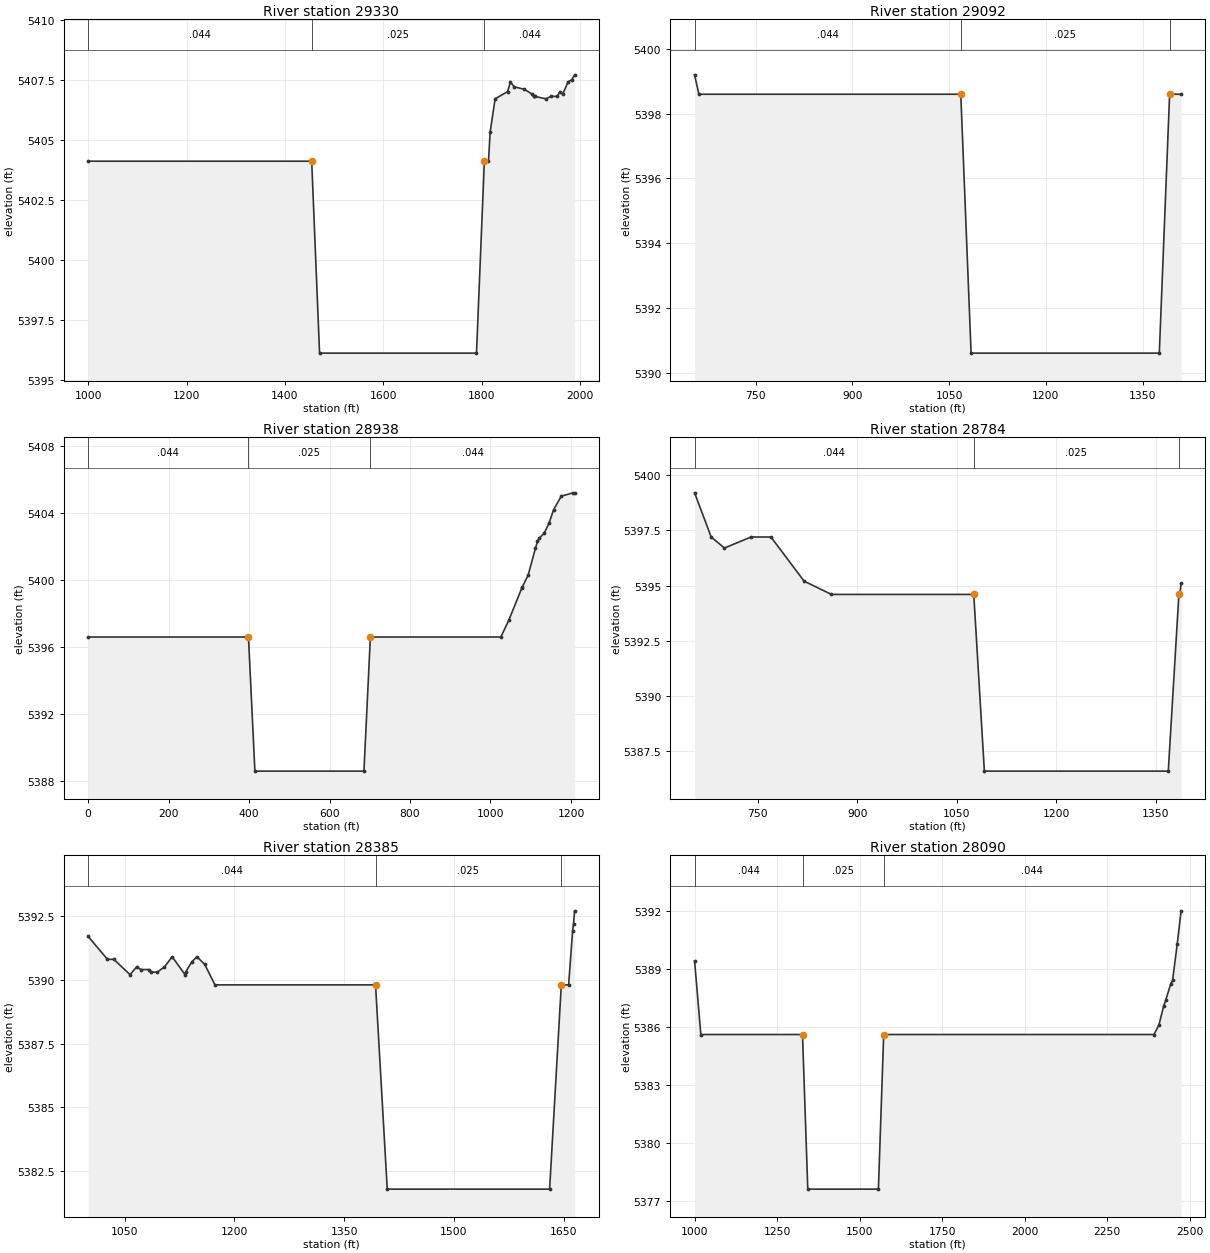
Type RM Length L Ch R = 1 ,29330   ,238,238,238
BEGIN DESCRIPTION:
Spur 10L
END DESCRIPTION:
#Sta/Elev= 24
    1000  5404.1  1454.5  5404.1  1470.5  5396.1  1789.5  5396.1  1805.5  5404.1
  1813.9  5404.1  1817.2  5405.3  1827.4  5406.7  1852.8    5407  1858.4  5407.4
  1866.1  5407.2  1886.3  5407.1  1902.5  5406.9  1906.9  5406.8  1907.2  5406.8
  1908.3  5406.8  1930.3  5406.7  1941.1  5406.8  1953.8  5406.8  1958.8    5407
  1964.9  5406.9  1975.5  5407.4  1983.2  5407.5    1989  5407.7
#Mann= 3 , 0 , 0
    1000    .044       0  1454.5    .025       0  1805.5    .044       0
#Block Obstruct= 2 , 0
         1140.51
Bank Sta=1454.5,1805.5
Sediment Elevation=0
Exp/Cntr=0.3,0.1

Type RM Length L Ch R = 1 ,29092   ,154,154,154
BEGIN DESCRIPTION:
Spur 10R
END DESCRIPTION:
#Sta/Elev= 7
     655  5399.2   661.7  5398.6    1068  5398.6    1084  5390.6    1376  5390.6
    1392  5398.6  1409.8  5398.6
#Mann= 3 , 0 , 0
     655    .044       0    1068    .025       0    1392    .044       0
Bank Sta=1068,1392
Sediment Elevation=0
Exp/Cntr=0.3,0.1

Type RM Length L Ch R = 1 ,28938   ,154,154,154
BEGIN DESCRIPTION:
Spur 9L
END DESCRIPTION:
#Sta/Elev= 19
       0  5396.6   398.5  5396.6   414.5  5388.6   685.5  5388.6   701.5  5396.6
  1025.8  5396.6  1045.5  5397.6  1077.5  5399.5  1079.5  5399.6  1093.7  5400.3
  1111.8  5401.9  1116.8  5402.3  1121.6  5402.5  1133.6  5402.8  1145.6  5403.4
    1157  5404.2    1176    5405  1205.1  5405.2  1209.1  5405.2
#Mann= 3 , 0 , 0
       0    .044       0   398.5    .025       0   701.5    .044       0
#Block Obstruct= 2 , 0
                          1386.4
Bank Sta=398.5,701.5
Sediment Elevation=0
Exp/Cntr=0.3,0.1

Type RM Length L Ch R = 1 ,28784   ,399,399,399
BEGIN DESCRIPTION:
Spur9R
END DESCRIPTION:
#Sta/Elev= 13
     655  5399.2     680  5397.2     700  5396.7     740  5397.2     770  5397.2
     820  5395.2   861.2  5394.6  1075.5  5394.6  1091.5  5386.6  1368.5  5386.6
  1384.5  5394.6  1386.1  5394.6  1387.8  5395.1
#Mann= 3 , 0 , 0
     655    .044       0  1075.5    .025       0  1384.5    .044       0
#Block Obstruct= 2 , 0
                          1386.4
Bank Sta=1075.5,1384.5
Sediment Elevation=0
Exp/Cntr=0.3,0.1

Type RM Length L Ch R = 1 ,28385   ,285,295,310
BEGIN DESCRIPTION:
Spur 8L,R
END DESCRIPTION:
#Sta/Elev= 25
    1000  5391.7  1026.5  5390.8  1035.2  5390.8  1057.3  5390.2  1066.3  5390.5
  1072.4  5390.4  1082.7  5390.4  1085.6  5390.3  1094.6  5390.3  1104.2  5390.5
    1115  5390.9  1132.5  5390.2  1133.3  5390.3  1141.7  5390.7  1148.8  5390.9
  1159.5  5390.6  1173.4  5389.8    1393  5389.8    1409  5381.8    1631  5381.8
    1647  5389.8    1657  5389.8  1662.4  5391.9  1663.7  5392.2  1665.2  5392.7
#Mann= 3 , 0 , 0
    1000    .044       0    1393    .025       0    1647    .044       0
Bank Sta=1393,1647
Sediment Elevation=0
Exp/Cntr=0.3,0.1

Type RM Length L Ch R = 1 ,28090   ,319,319,319
BEGIN DESCRIPTION:
Spur 7L
END DESCRIPTION:
#Sta/Elev= 14
    1000  5389.4    1019  5385.6    1327  5385.6    1343  5377.6    1557  5377.6
    1573  5385.6    2392  5385.6    2407  5386.1  2421.7  5387.1    2428  5387.4
  2442.3  5388.2  2448.3  5388.4  2462.5  5390.3  2474.1    5392
#Mann= 3 , 0 , 0
    1000    .044       0    1327    .025       0    1573    .044       0
#Block Obstruct= 2 , 0
                            1600
Bank Sta=1327,1573
Sediment Elevation=0
Exp/Cntr=0.3,0.1

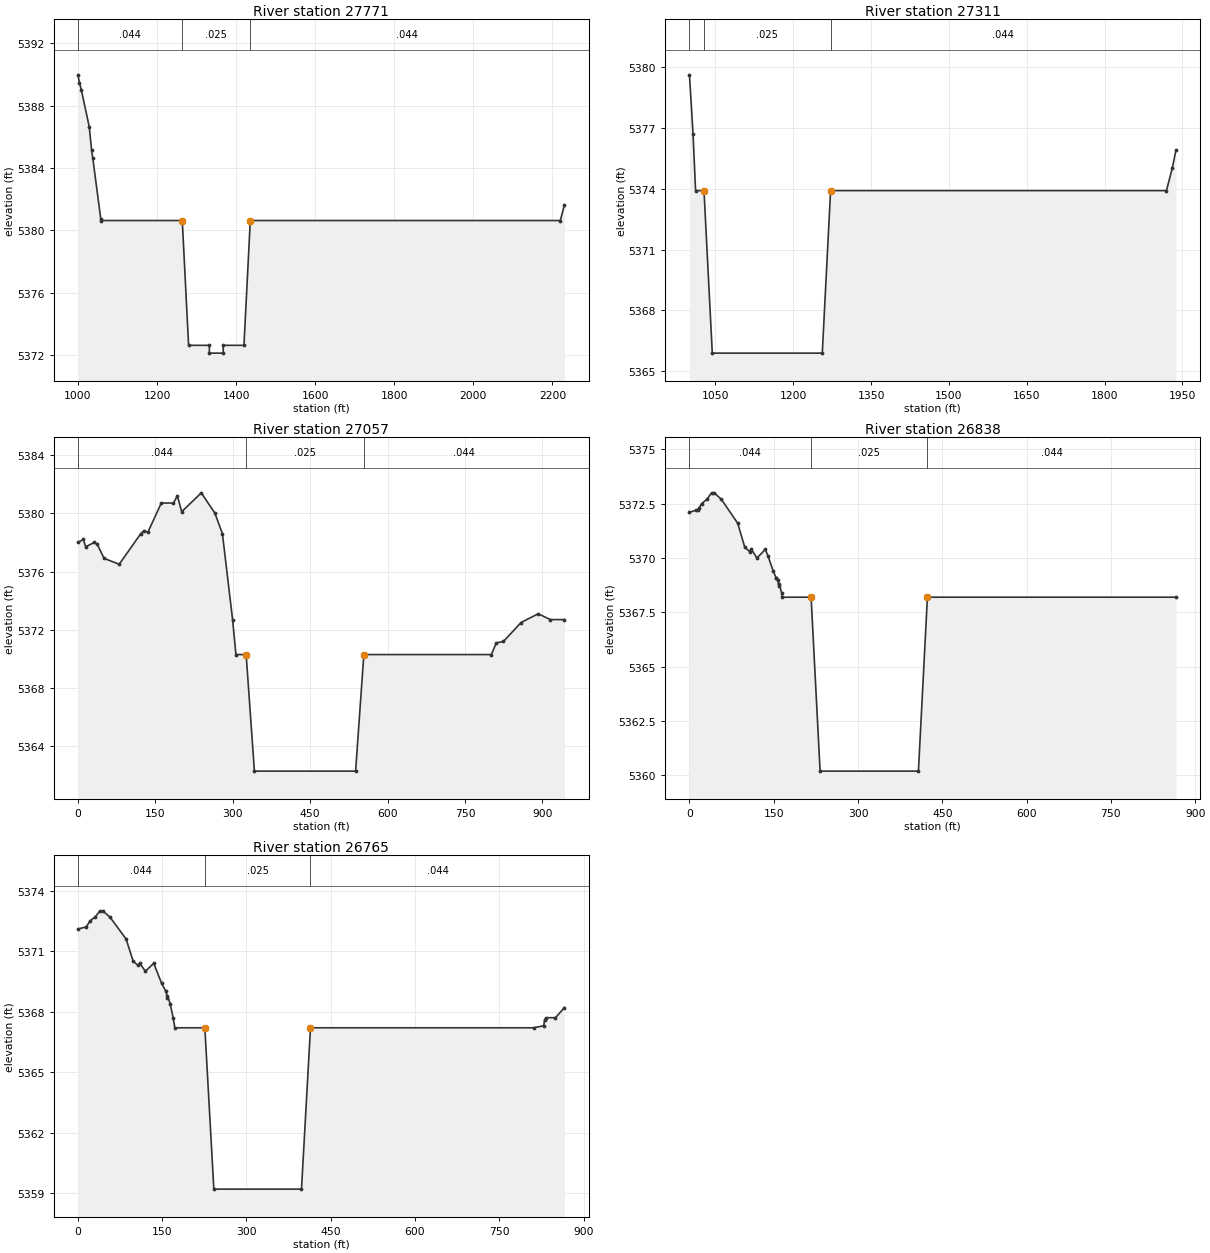
Type RM Length L Ch R = 1 ,27771   ,530,460,430
BEGIN DESCRIPTION:
GCS4 Crest
END DESCRIPTION:
#Sta/Elev= 18
    1000 5389.97 1004.07 5389.47 1009.06 5388.97 1028.76 5386.64 1034.74 5385.13
 1037.66 5384.64 1057.96 5380.72 1058.37 5380.63    1264 5380.63    1280 5372.63
  1332.5 5372.63  1332.5 5372.13  1367.5 5372.13  1367.5 5372.63    1420 5372.63
    1436 5380.63 2219.91 5380.63 2230.28 5381.63
#Mann= 3 , 0 , 0
    1000    .044       0    1264    .025       0    1436    .044       0
Bank Sta=1264,1436
Sediment Elevation=0
Exp/Cntr=0.3,0.1

Type RM Length L Ch R = 1 ,27311   ,254,254,254
BEGIN DESCRIPTION:
Spur6L
END DESCRIPTION:
#Sta/Elev= 10
    1000  5379.6  1006.9  5376.7  1011.8  5373.9    1028  5373.9    1044  5365.9
    1256  5365.9    1272  5373.9  1919.3  5373.9  1930.5    5375  1937.7  5375.9
#Mann= 3 , 0 , 0
    1000    .044       0    1028    .025       0    1272    .044       0
Bank Sta=1028,1272
Sediment Elevation=0
Exp/Cntr=0.3,0.1

Type RM Length L Ch R = 1 ,27057   ,219,219,219
BEGIN DESCRIPTION:
Spur 5L,R
END DESCRIPTION:
#Sta/Elev= 30
       0    5378    10.6  5378.2    15.1  5377.7    32.2    5378      37  5377.9
    50.8  5376.9    80.1  5376.5   121.9  5378.6     128  5378.8   135.7  5378.7
   161.6  5380.7   185.2  5380.7   192.8  5381.2   201.1  5380.1   239.1  5381.4
   265.5    5380     280  5378.6   299.7  5372.7   306.2  5370.3     326  5370.3
     342  5362.3     538  5362.3     554  5370.3   801.1  5370.3   810.5  5371.1
   824.5  5371.2   858.5  5372.5   891.8  5373.1   915.1  5372.7   942.5  5372.7
#Mann= 3 , 0 , 0
       0    .044       0     326    .025       0     554    .044       0
Bank Sta=326,554
Sediment Elevation=0
Exp/Cntr=0.3,0.1

Type RM Length L Ch R = 1 ,26838   ,73,73,73
BEGIN DESCRIPTION:
Spur4R
END DESCRIPTION:
#Sta/Elev= 29
       0  5372.1    11.2  5372.2    14.9  5372.2    17.1  5372.3    21.6  5372.5
    30.9  5372.7    39.4    5373      44    5373    56.8  5372.7    85.9  5371.6
    98.4  5370.5   107.1  5370.3   110.4  5370.4   120.1    5370     135  5370.4
   139.7  5370.1   149.1  5369.4     154  5369.1   154.3  5369.1   156.9    5369
   159.1  5368.7   159.4  5368.8   164.2  5368.4   165.1  5368.2   216.5  5368.2
   232.5  5360.2   407.5  5360.2   423.5  5368.2   865.9  5368.2
#Mann= 3 , 0 , 0
       0    .044       0   216.5    .025       0   423.5    .044       0
Bank Sta=216.5,423.5
Sediment Elevation=0
Exp/Cntr=0.3,0.1

Type RM Length L Ch R = 1 ,26765   ,293,293,305
BEGIN DESCRIPTION:
Spur 4L
END DESCRIPTION:
#Sta/Elev= 30
       0  5372.1    14.9  5372.2    21.6  5372.5    30.9  5372.7    39.4    5373
      44    5373    56.8  5372.7    85.9  5371.6    98.4  5370.5   107.1  5370.3
   110.4  5370.4   120.1    5370     135  5370.4   149.1  5369.4   156.9    5369
   159.1  5368.7   159.4  5368.8   164.2  5368.4   169.6  5367.7   172.6  5367.2
     226  5367.2     242  5359.2     398  5359.2     414  5367.2     811  5367.2
   829.1  5367.3   830.7  5367.6   833.8  5367.7     850  5367.7   865.9  5368.2
#Mann= 3 , 0 , 0
       0    .044       0     226    .025       0     414    .044       0
Bank Sta=226,414
Exp/Cntr=0.3,0.1

--- NBCalab.g06 (geometry) ---

Geom Title=NB Calab, Existing Cond-NGVD29 FINAL
Program Version=3.12

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
River Reach=Calabacillas    ,N Branch