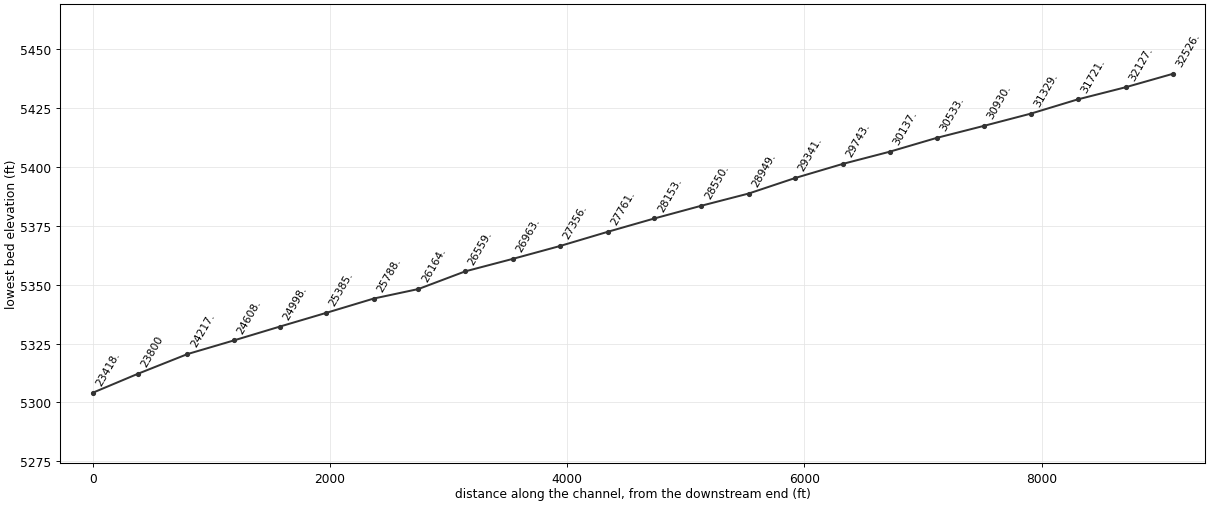
HEC-RAS study NBCalab.prj: North Branch Calabacillas Arroyo

--- NBCalab.g06 (geometry) --- (continued)

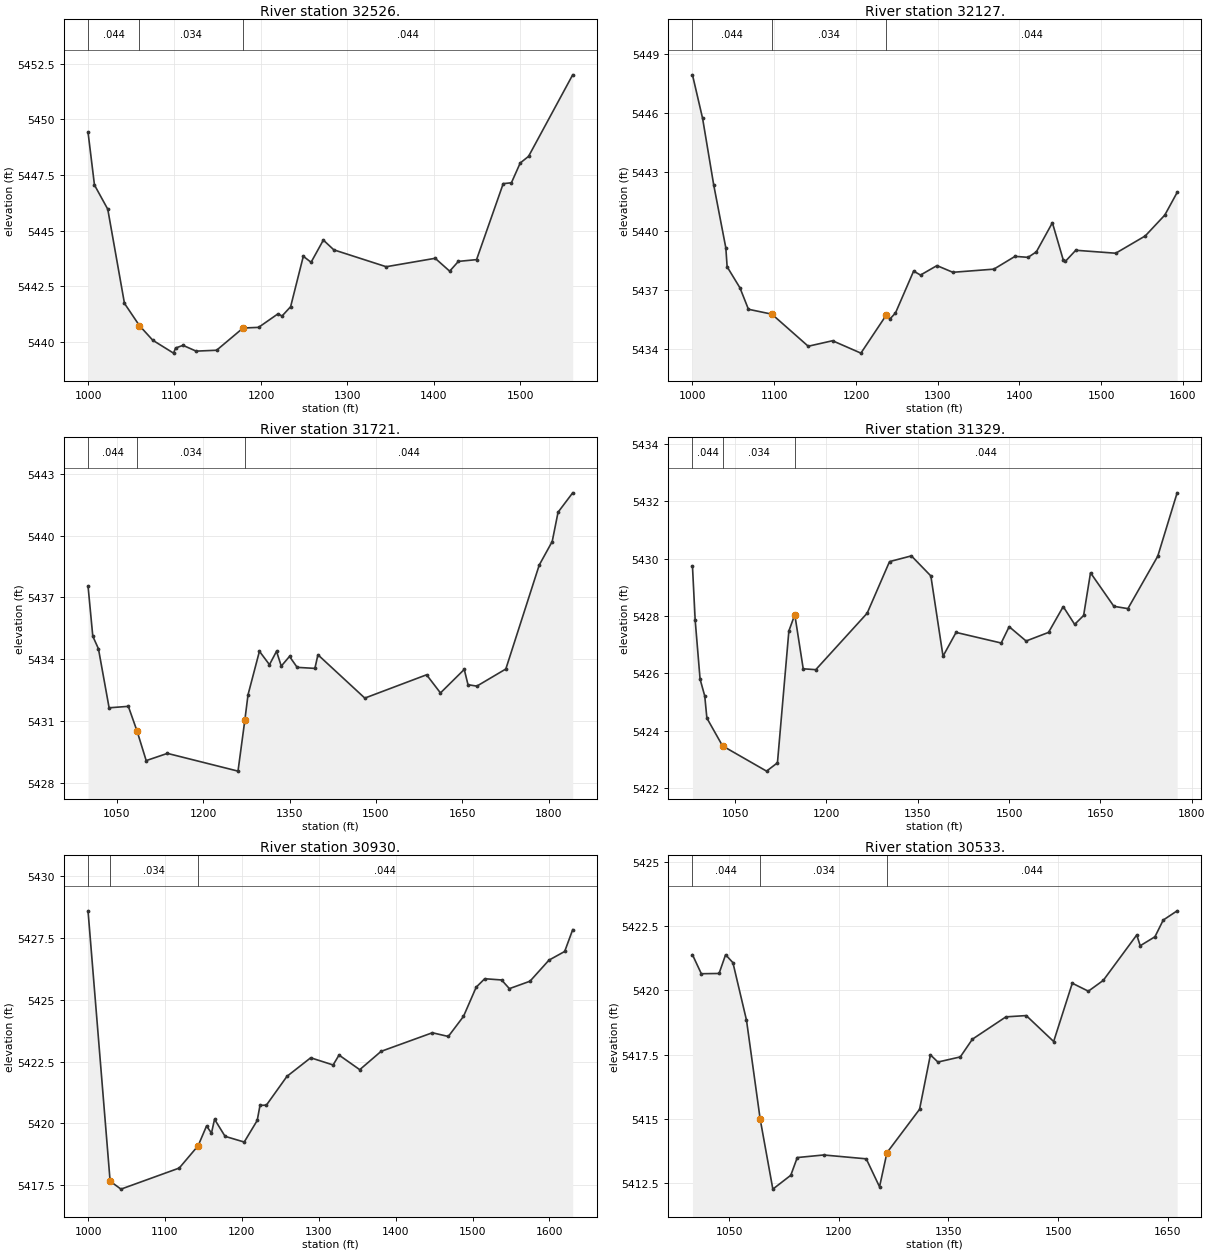
Type RM Length L Ch R = 1 ,32526.  ,400,399,380
#Sta/Elev= 30
    1000 5449.43 1007.45 5447.05 1022.83 5445.96 1042.15 5441.72 1059.44 5440.72
  1074.9 5440.06 1098.88 5439.48 1101.28 5439.71 1109.89 5439.83 1125.02 5439.57
 1148.71 5439.61  1179.3 5440.61 1197.24 5440.64 1219.74 5441.25 1224.36 5441.15
 1234.31 5441.57 1248.99 5443.84 1257.98 5443.57 1272.16 5444.57 1284.27 5444.13
 1344.85 5443.37 1401.51 5443.75 1418.27 5443.17 1428.33 5443.61 1449.37 5443.69
 1480.18 5447.11 1489.67 5447.15 1499.85 5448.04 1509.51 5448.34 1560.54 5452.01
#Mann= 3 , 0 , 0
    1000    .044       0 1059.44    .034       0  1179.3    .044       0
Bank Sta=1059.44,1179.3
Sediment Elevation=0
Exp/Cntr=0.3,0.1

Type RM Length L Ch R = 1 ,32127.  ,410,406,380
#Sta/Elev= 30
    1000 5447.92 1012.37 5445.71 1025.96 5442.33 1040.82 5439.12  1042.4 5438.16
 1058.09 5437.09 1068.47    5436 1097.18 5435.75 1141.62 5434.12 1171.35  5434.4
 1206.06 5433.77 1237.19 5435.71 1241.39  5435.5 1248.34 5435.81 1270.55 5437.94
 1278.99 5437.74 1299.09 5438.22 1318.55 5437.88 1368.71 5438.04 1394.61 5438.69
 1410.55 5438.64  1420.7 5438.92 1440.32  5440.4 1453.79 5438.48 1456.06 5438.43
  1468.9    5439 1517.81 5438.85 1553.95 5439.73 1577.84 5440.79 1592.92 5441.94
#Mann= 3 , 0 , 0
    1000    .044       0 1097.18    .034       0 1237.19    .044       0
Bank Sta=1097.18,1237.19
Sediment Elevation=0
Exp/Cntr=0.3,0.1

Type RM Length L Ch R = 1 ,31721.  ,390,392,410
#Sta/Elev= 30
    1000 5437.56 1008.28 5435.12 1018.11 5434.51 1036.62 5431.65 1070.03 5431.72
 1085.31 5430.51 1101.04 5429.09  1137.9 5429.44 1260.53 5428.58 1272.39 5431.05
 1277.92 5432.28 1297.75 5434.39 1315.17 5433.74 1327.43 5434.39 1335.67 5433.67
 1349.99 5434.14 1363.28 5433.61 1394.07 5433.56 1399.37 5434.22 1480.79 5432.12
 1588.09 5433.25 1612.18 5432.37 1653.53 5433.51 1660.04 5432.77 1675.39  5432.7
 1725.73 5433.53 1783.78 5438.57 1806.31 5439.71 1816.47 5441.13 1841.89 5442.07
#Mann= 3 , 0 , 0
    1000    .044       0 1085.31    .034       0 1272.39    .044       0
Bank Sta=1085.31,1272.39
Sediment Elevation=0
Exp/Cntr=0.3,0.1

Type RM Length L Ch R = 1 ,31329.  ,420,399,330
#Sta/Elev= 30
     980 5429.74  984.44 5427.86   992.5  5425.8 1000.18 5425.21 1003.68 5424.44
 1029.44 5423.47 1101.73 5422.59  1119.6 5422.88 1138.36 5427.48 1148.09 5428.05
 1161.93 5426.16 1182.55 5426.13 1266.97  5428.1  1303.7  5429.9 1339.62  5430.1
  1371.6  5429.4 1391.58  5426.6 1412.99 5427.43 1487.15 5427.06 1500.22 5427.63
 1528.04 5427.13  1564.9 5427.43 1589.02 5428.33 1607.83 5427.71 1622.54 5428.02
 1633.87 5429.51 1672.25 5428.34  1695.3 5428.26 1744.34 5430.09 1776.16  5432.3
#Mann= 3 , 0 , 0
     980    .044       0 1029.44    .034       0 1148.09    .044       0
#Block Obstruct= 2 , 0
                         1654.63
Bank Sta=1029.44,1148.09
Sediment Elevation=0
Exp/Cntr=0.3,0.1

Type RM Length L Ch R = 1 ,30930.  ,400,397,400
#Sta/Elev= 30
    1000 5428.58 1028.73 5417.67 1042.85 5417.35 1118.59  5418.2 1143.16  5419.1
 1154.14  5419.9 1160.52 5419.61 1164.52 5420.17 1178.22 5419.48  1203.1 5419.25
 1219.99 5420.12 1223.64 5420.73 1231.97 5420.74 1258.66  5421.9 1289.55 5422.65
 1318.71 5422.36 1326.38 5422.76 1353.32 5422.17 1381.11 5422.91 1447.77 5423.66
  1468.5 5423.51 1488.22 5424.32 1504.76  5425.5 1515.86 5425.84 1537.76 5425.79
 1547.93 5425.44  1574.7 5425.74 1599.36 5426.59 1619.81 5426.94 1630.23 5427.82
#Mann= 3 , 0 , 0
    1000    .044       0 1028.73    .034       0 1143.16    .044       0
Bank Sta=1028.73,1143.16
Sediment Elevation=0
Exp/Cntr=0.3,0.1

Type RM Length L Ch R = 1 ,30533.  ,380,396,450
#Sta/Elev= 30
    1000 5421.39 1012.11 5420.65 1036.37 5420.66  1045.3 5421.39 1055.32 5421.08
 1073.88 5418.84 1092.56 5414.99 1109.91 5412.26 1134.45  5412.8 1143.29 5413.49
 1179.43 5413.59 1237.64 5413.44  1255.8 5412.35 1265.95 5413.68 1310.53 5415.37
 1325.35 5417.49 1335.62 5417.21 1366.23 5417.41 1382.75  5418.1 1428.63 5418.97
 1456.38 5419.02 1493.88 5418.01 1519.37 5420.28 1541.31 5419.97 1561.69 5420.39
  1607.5 5422.16 1612.25 5421.74 1632.38 5422.09  1643.7 5422.74 1662.72  5423.1
#Mann= 3 , 0 , 0
    1000    .044       0 1092.56    .034       0 1265.95    .044       0
Bank Sta=1092.56,1265.95
Sediment Elevation=0
Exp/Cntr=0.3,0.1

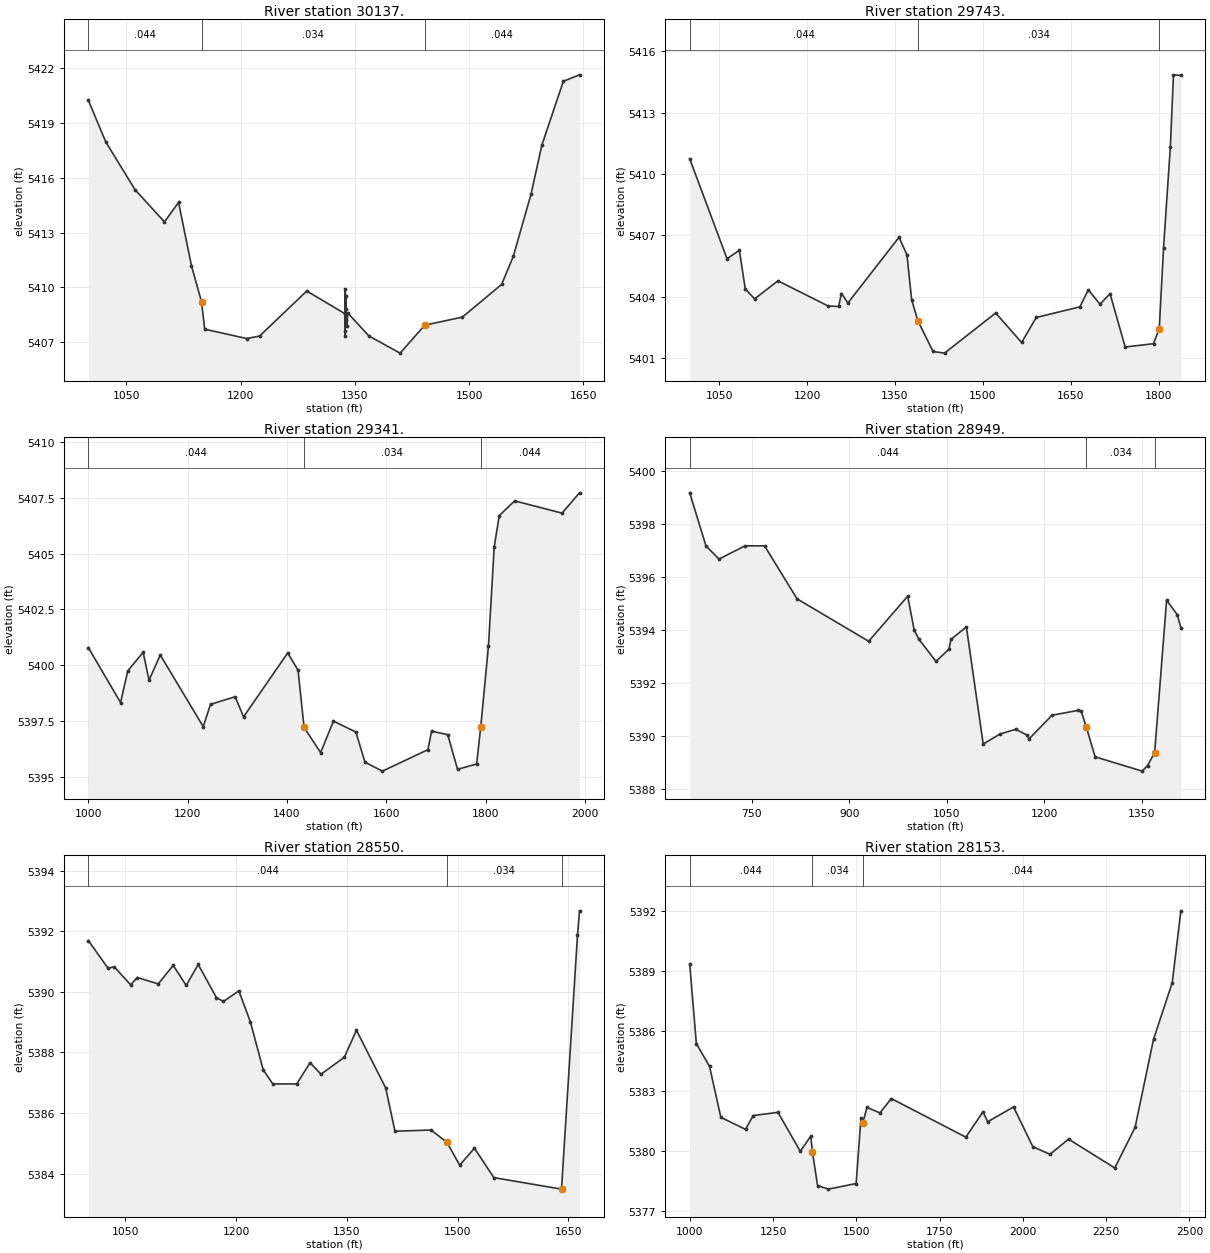
Type RM Length L Ch R = 1 ,30137.  ,400,394,350
#Sta/Elev= 30
    1000 5420.24 1022.85 5417.96  1061.2 5415.35 1099.92 5413.58 1118.43 5414.65
 1135.38 5411.18 1148.64  5409.2  1152.7 5407.71 1207.88  5407.2  1224.7 5407.33
 1286.74  5409.8 1337.17 5408.55 1337.18 5407.34  1337.2 5407.63 1337.23 5409.91
 1337.89  5408.2 1338.17 5409.54 1338.31 5408.82 1339.19  5407.9 1340.56  5408.6
 1368.28 5407.34 1409.24  5406.4 1441.66 5407.93 1491.02 5408.37 1542.56 5410.16
 1557.83 5411.69 1581.17  5415.1 1595.35 5417.78 1623.57 5421.28 1644.81 5421.63
#Mann= 3 , 0 , 0
    1000    .044       0 1148.64    .034       0 1441.66    .044       0
Bank Sta=1148.64,1441.66
Sediment Elevation=0
Exp/Cntr=0.3,0.1

Type RM Length L Ch R = 1 ,29743.  ,390,402,420
#Sta/Elev= 30
    1000 5410.74 1063.65 5405.86  1084.7 5406.27 1094.76 5404.38 1110.69  5403.9
 1150.45 5404.78  1236.1 5403.55  1253.9 5403.53 1258.69 5404.16 1269.72  5403.7
 1356.88 5406.91 1370.34 5406.05 1378.38 5403.86 1388.96 5402.83 1414.91 5401.33
 1434.47 5401.25 1521.58 5403.21 1565.88 5401.77 1590.71 5402.99 1665.14 5403.51
 1679.54 5404.34 1699.36 5403.64  1716.6 5404.15  1742.4 5401.55  1790.7 5401.71
  1800.5 5402.45  1807.8  5406.4  1819.4 5411.33  1824.7 5414.84  1837.3 5414.81
#Mann= 3 , 0 , 0
    1000    .044       0 1388.96    .034       0  1800.5    .044       0
#Block Obstruct= 2 , 0
         1357.19
Bank Sta=1388.96,1800.5
Sediment Elevation=0
Exp/Cntr=0.3,0.1

Type RM Length L Ch R = 1 ,29341.  ,320,392,455
#Sta/Elev= 30
    1000 5400.79 1064.88 5398.33 1079.37 5399.75 1110.38 5400.58 1122.21 5399.33
 1144.79 5400.46 1231.35 5397.25 1245.97 5398.25 1295.58 5398.59 1312.55 5397.69
 1401.38 5400.55 1422.22 5399.78 1434.35 5397.22 1467.66 5396.09 1493.57  5397.5
 1538.66 5397.01 1557.01 5395.66 1592.14 5395.26  1683.7 5396.22 1691.12 5397.05
 1723.68 5396.89 1743.43 5395.34 1781.83 5395.58 1790.12 5397.24 1805.73 5400.88
 1817.22  5405.3 1827.38  5406.7  1858.4 5407.36  1953.8 5406.81    1989 5407.72
#Mann= 3 , 0 , 0
    1000    .044       0 1434.35    .034       0 1790.12    .044       0
#Block Obstruct= 2 , 0
         1140.51
Bank Sta=1434.35,1790.12
Sediment Elevation=0
Exp/Cntr=0.3,0.1

Type RM Length L Ch R = 1 ,28949.  ,350,399,410
BEGIN DESCRIPTION:
Cut from Goodwin (2003) Mapping
END DESCRIPTION:
#Sta/Elev= 30
     655 5399.17     680 5397.17     700 5396.67     740 5397.17     770 5397.17
     820 5395.17     930 5393.57     990 5395.27    1000 5393.99 1007.41 5393.64
 1033.41 5392.81 1053.45 5393.27 1056.42 5393.64  1080.2 5394.11 1106.03 5389.69
  1131.8 5390.07 1156.18 5390.25    1174 5390.02 1176.33 5389.88 1211.75 5390.78
  1251.7 5390.96 1256.59 5390.94 1264.58 5390.32 1278.01 5389.21  1350.3 5388.67
 1358.55 5388.88 1369.47 5389.37 1387.84 5395.12 1404.29 5394.57 1409.75 5394.08
#Mann= 3 , 0 , 0
     655    .044       0 1264.58    .034       0 1369.47    .044       0
#Block Obstruct= 2 , 0
                          1386.4
Bank Sta=1264.58,1369.47
Sediment Elevation=0
Exp/Cntr=0.3,0.1

Type RM Length L Ch R = 1 ,28550.  ,420,397,400
BEGIN DESCRIPTION:
Cut from Goodwin (2003) Mapping
END DESCRIPTION:
#Sta/Elev= 30
    1000 5391.69 1026.51 5390.78 1035.18 5390.82 1057.26 5390.23 1066.33 5390.47
 1094.63 5390.26 1114.97 5390.87 1132.49 5390.21  1148.8  5390.9 1173.38 5389.81
 1182.92 5389.68 1203.83 5390.03 1219.55    5389 1236.76 5387.43 1249.75 5386.96
 1282.19 5386.96 1300.35 5387.66 1315.07 5387.28 1346.67 5387.84 1363.09 5388.73
 1402.65 5386.83 1415.26  5385.4 1463.98 5385.44 1485.81 5385.03 1502.86 5384.28
 1522.86 5384.84 1549.19 5383.87 1640.81 5383.49 1662.43 5391.86 1665.19 5392.67
#Mann= 3 , 0 , 0
    1000    .044       0 1485.81    .034       0 1640.81    .044       0
Bank Sta=1485.81,1640.81
Sediment Elevation=0
Exp/Cntr=0.3,0.1

Type RM Length L Ch R = 1 ,28153.  ,500,392,370
BEGIN DESCRIPTION:
Cut from Goodwin (2003) Mapping
END DESCRIPTION:
#Sta/Elev= 30
    1000 5389.35 1020.04 5385.36 1059.53 5384.22 1093.51 5381.67 1167.53 5381.07
 1190.86 5381.76 1264.94 5381.92 1331.85 5379.97 1363.38 5380.73 1368.53 5379.92
 1383.81 5378.26 1416.42 5378.08 1499.63 5378.36 1513.92 5381.64 1519.18 5381.37
 1532.11 5382.17 1571.01 5381.89 1605.08 5382.61 1828.77 5380.68 1880.28 5381.95
  1894.3 5381.45 1971.99 5382.19 2029.93  5380.2 2081.27 5379.82  2137.1 5380.58
 2275.77 5379.14 2336.79 5381.17 2392.04 5385.57 2448.34 5388.41 2474.11    5392
#Mann= 3 , 0 , 0
    1000    .044       0 1368.53    .034       0 1519.18    .044       0
#Block Obstruct= 2 , 0
                            1600
Bank Sta=1368.53,1519.18
Sediment Elevation=0
Exp/Cntr=0.3,0.1

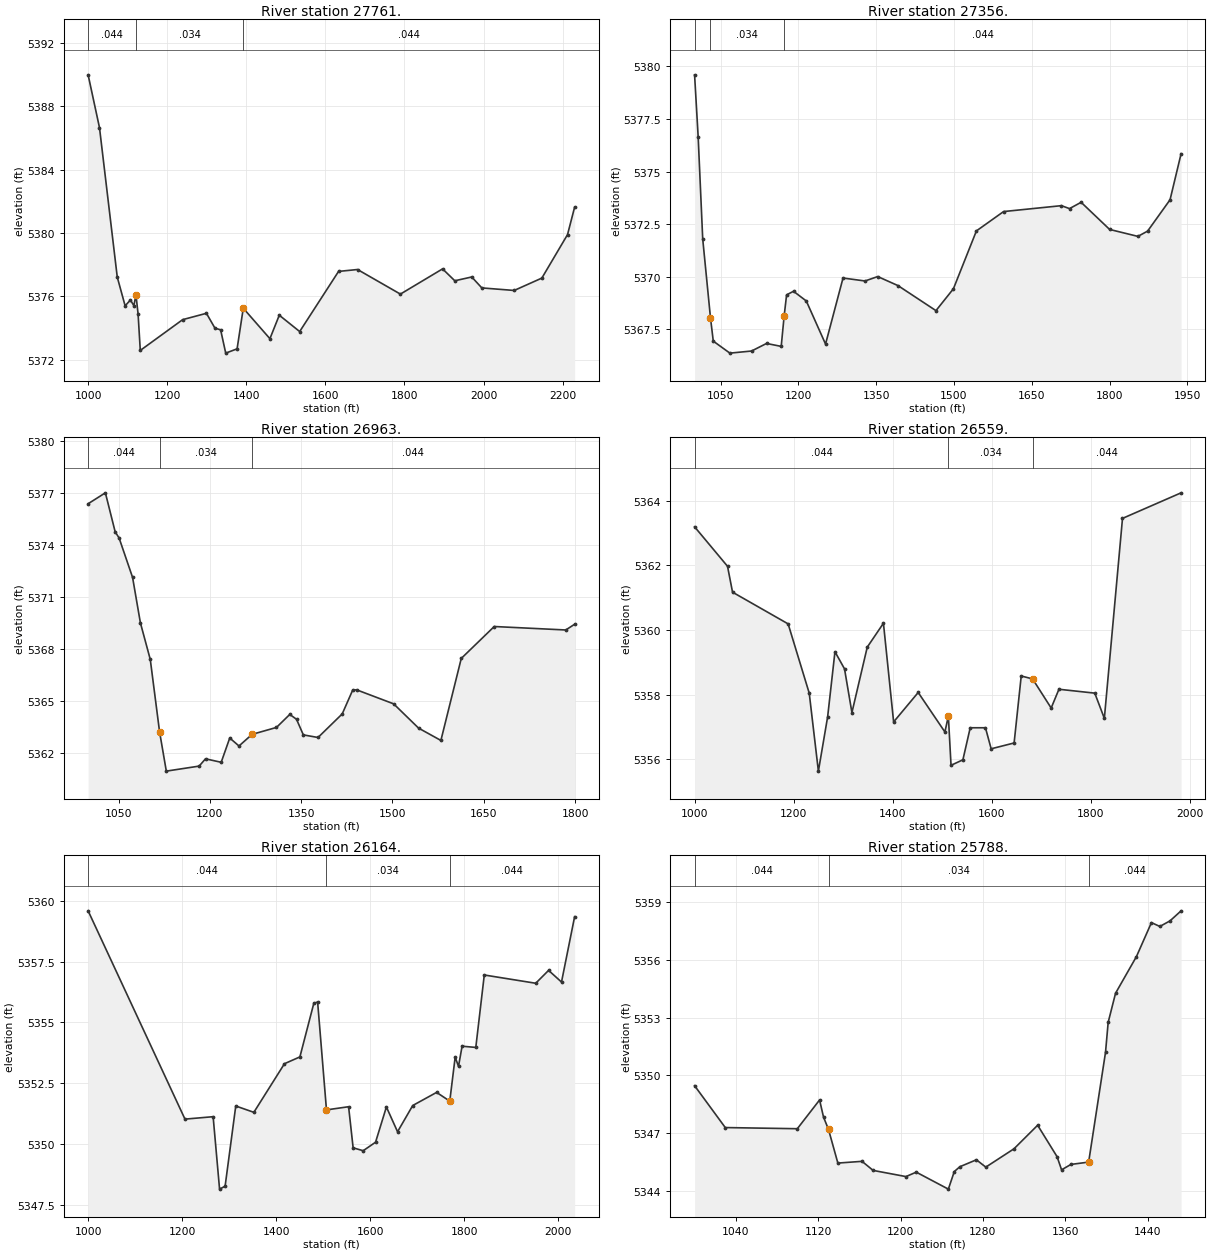
Type RM Length L Ch R = 1 ,27761.  ,450,405,360
BEGIN DESCRIPTION:
Cut from Goodwin (2003) Mapping
END DESCRIPTION:
#Sta/Elev= 30
    1000 5389.97 1028.76 5386.64 1073.71 5377.22 1093.61 5375.41 1106.97 5375.78
 1115.68 5375.42 1120.99  5376.1 1126.35  5374.9 1131.93  5372.6 1239.07 5374.54
  1299.2 5374.94  1320.8    5374 1335.07  5373.9 1347.98 5372.43 1376.74  5372.7
 1392.37 5375.26 1459.72 5373.34 1483.42 5374.82 1534.99 5373.79 1633.33 5377.58
 1681.29  5377.7 1789.69 5376.15 1896.35 5377.74 1927.28 5376.99 1970.09 5377.23
 1995.61 5376.54 2077.45 5376.38 2147.41 5377.16 2212.34  5379.9 2230.28 5381.63
#Mann= 3 , 0 , 0
    1000    .044       0 1120.99    .034       0 1392.37    .044       0
#Block Obstruct= 2 , 0
                         1667.38
Bank Sta=1120.99,1392.37
Sediment Elevation=0
Exp/Cntr=0.3,0.1

Type RM Length L Ch R = 1 ,27356.  ,410,393,310
BEGIN DESCRIPTION:
Cut from Goodwin (2003) Mapping
END DESCRIPTION:
#Sta/Elev= 30
    1000  5379.6 1006.91 5376.65 1015.67  5371.8 1030.67 5368.04 1036.04 5366.94
 1068.06 5366.37 1109.81 5366.47 1138.72 5366.83 1166.97 5366.69  1172.7 5368.15
 1177.35 5369.14 1190.67 5369.31  1215.3 5368.85 1252.44  5366.8 1286.13 5369.94
 1328.51  5369.8    1353 5370.01 1392.07 5369.58 1465.26 5368.39 1498.91 5369.43
 1543.21 5372.18 1595.61  5373.1 1707.02 5373.38 1722.65 5373.24 1745.05 5373.54
 1799.98 5372.25 1854.45 5371.92 1873.17 5372.17 1916.44 5373.66 1937.73 5375.85
#Mann= 3 , 0 , 0
    1000    .044       0 1030.67    .034       0  1172.7    .044       0
Bank Sta=1030.67,1172.7
Sediment Elevation=0
Exp/Cntr=0.3,0.1

Type RM Length L Ch R = 1 ,26963.  ,400,404,440
BEGIN DESCRIPTION:
Cut from Goodwin (2003) Mapping
END DESCRIPTION:
#Sta/Elev= 30
    1000  5376.4 1028.36 5377.03 1044.44 5374.78 1050.85 5374.43 1073.05 5372.15
  1085.9 5369.53 1102.11 5367.42 1117.37 5363.25 1128.46 5360.98 1182.41 5361.27
 1192.84 5361.69 1218.62 5361.49 1232.66 5362.89 1247.85 5362.43 1269.34  5363.1
 1309.42  5363.5 1331.28 5364.25 1342.38 5363.97 1353.53 5363.07 1377.71 5362.92
 1417.45 5364.28  1434.6 5365.65    1441 5365.67 1501.93 5364.86 1542.89 5363.46
 1579.53 5362.75 1613.01 5367.48 1667.17 5369.32 1784.67 5369.12 1799.22 5369.45
#Mann= 3 , 0 , 0
    1000    .044       0 1117.37    .034       0 1269.34    .044       0
Bank Sta=1117.37,1269.34
Sediment Elevation=0
Exp/Cntr=0.3,0.1

Type RM Length L Ch R = 1 ,26559.  ,380,395,440
BEGIN DESCRIPTION:
Cut from Goodwin (2003) Mapping
END DESCRIPTION:
#Sta/Elev= 30
    1000 5363.19 1066.54 5361.97 1076.66 5361.17 1188.96 5360.19 1231.57 5358.05
 1250.09 5355.64 1268.78 5357.32 1283.55 5359.33 1302.85  5358.8 1317.82 5357.45
 1348.75 5359.47 1381.47 5360.21 1402.06 5357.16 1451.67 5358.07 1505.64 5356.85
  1512.6 5357.34    1518 5355.82 1541.98 5355.99 1556.77 5356.98 1587.56 5356.98
 1599.05 5356.33 1645.43 5356.51  1659.8 5358.58 1682.73 5358.49 1720.27 5357.59
 1735.98 5358.17 1808.38 5358.05  1827.7 5357.27 1864.36 5363.45 1982.71 5364.24
#Mann= 3 , 0 , 0
    1000    .044       0  1512.6    .034       0 1682.73    .044       0
#Block Obstruct= 2 , 0
         1359.75
Bank Sta=1512.6,1682.73
Sediment Elevation=0
Exp/Cntr=0.3,0.1

Type RM Length L Ch R = 1 ,26164.  ,250,376,560
BEGIN DESCRIPTION:
Cut from Goodwin (2003) Mapping
END DESCRIPTION:
#Sta/Elev= 30
    1000 5359.59 1206.02 5351.02 1265.92 5351.12  1279.6 5348.14  1291.4 5348.26
 1314.05 5351.56 1352.54  5351.3 1417.64  5353.3 1450.47 5353.58    1480 5355.78
 1488.18 5355.84 1506.99  5351.4 1554.05 5351.53  1563.7 5349.84 1585.06 5349.72
 1611.39 5350.07 1634.46 5351.52 1658.19  5350.5 1690.46 5351.58 1741.26 5352.12
 1769.26 5351.76 1780.74 5353.57 1787.84 5353.19 1795.45 5354.02 1824.61 5353.97
 1842.67 5356.95 1952.08 5356.61 1979.44 5357.14 2006.92 5356.66 2034.82 5359.35
#Mann= 3 , 0 , 0
    1000    .044       0 1506.99    .034       0 1769.26    .044       0
#Block Obstruct= 2 , 0
         1487.32
Bank Sta=1506.99,1769.26
Sediment Elevation=0
Exp/Cntr=0.3,0.1

Type RM Length L Ch R = 1 ,25788.  ,380,403,440
BEGIN DESCRIPTION:
Cut from Goodwin (2003) Mapping
END DESCRIPTION:
#Sta/Elev= 30
    1000 5349.47  1029.8  5347.3 1099.75 5347.24 1121.38 5348.73 1125.22 5347.84
 1130.06  5347.2 1139.13 5345.46 1162.61 5345.55 1173.35 5345.08 1205.25 5344.76
 1215.25 5344.99 1246.43 5344.11 1252.18 5345.02 1257.56 5345.27 1273.65 5345.63
 1282.79 5345.25 1310.16  5346.2 1333.12 5347.42    1352 5345.79 1356.37 5345.11
 1365.45 5345.39 1382.66 5345.51 1399.04  5351.2 1401.61 5352.75 1408.78 5354.26
 1429.07 5356.16 1443.63 5357.92 1451.77 5357.72 1461.68 5358.01 1472.42 5358.53
#Mann= 3 , 0 , 0
    1000    .044       0 1130.06    .034       0 1382.66    .044       0
#Block Obstruct= 2 , 0
         1110.19
Bank Sta=1130.06,1382.66
Sediment Elevation=0
Exp/Cntr=0.3,0.1

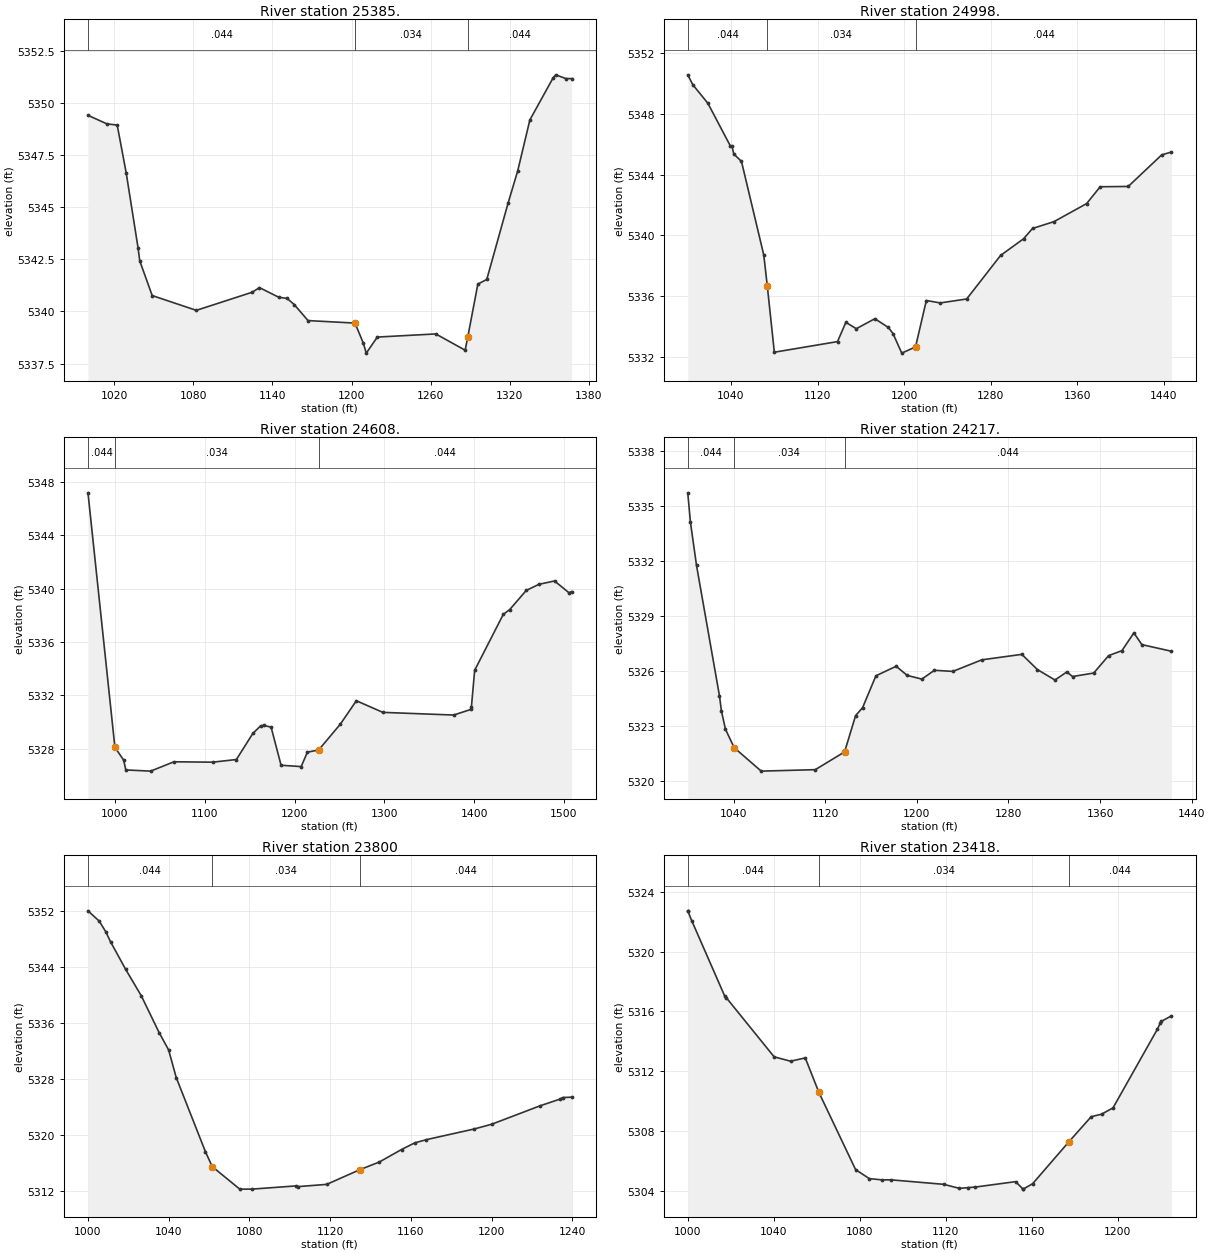
Type RM Length L Ch R = 1 ,25385.  ,450,387,350
BEGIN DESCRIPTION:
Cut from Goodwin (2003) Mapping
END DESCRIPTION:
#Sta/Elev= 30
    1000  5349.4 1014.34 5348.99 1022.19 5348.93 1029.01 5346.64 1038.04 5343.03
  1039.3 5342.42 1048.73 5340.76 1082.22 5340.05 1124.66 5340.92 1130.14 5341.14
 1144.72 5340.68 1151.14 5340.62 1156.49 5340.33 1166.99 5339.56 1202.64 5339.44
 1208.92 5338.48 1211.19    5338 1219.57 5338.77 1263.94 5338.92 1286.21 5338.14
 1288.26 5338.79 1295.85 5341.31 1302.61 5341.53 1318.79 5345.19 1326.06 5346.73
 1335.33 5349.18    1353  5351.2 1354.94 5351.34 1362.63 5351.16 1366.99 5351.16
#Mann= 3 , 0 , 0
    1000    .044       0 1202.64    .034       0 1288.26    .044       0
Bank Sta=1202.64,1288.26
Sediment Elevation=0
Exp/Cntr=0.3,0.1

Type RM Length L Ch R = 1 ,24998.  ,440,390,330
BEGIN DESCRIPTION:
Cut from Goodwin (2003) Mapping
END DESCRIPTION:
#Sta/Elev= 30
    1000 5350.59 1004.75 5349.93 1018.56 5348.72 1039.47 5345.89 1040.91 5345.87
 1042.61 5345.37 1049.68 5344.88 1070.29 5338.71 1073.57 5336.66 1080.07  5332.3
 1138.49    5333 1146.22 5334.27 1155.86 5333.85 1173.03 5334.51 1185.57 5333.93
  1189.8 5333.53 1197.92 5332.24 1210.64 5332.65 1220.65 5335.71 1233.46 5335.55
 1257.93 5335.81 1289.28 5338.68 1310.55 5339.78 1318.84 5340.46 1338.67 5340.91
 1368.87  5342.1 1381.41 5343.21 1407.34 5343.23 1438.26 5345.31 1447.25  5345.5
#Mann= 3 , 0 , 0
    1000    .044       0 1073.57    .034       0 1210.64    .044       0
Bank Sta=1073.57,1210.64
Sediment Elevation=0
Exp/Cntr=0.3,0.1

Type RM Length L Ch R = 1 ,24608.  ,440,391,340
BEGIN DESCRIPTION:
Cut from Goodwin (2003) Mapping
END DESCRIPTION:
#Sta/Elev= 30
     970 5347.17    1000 5328.11 1009.78 5327.15 1012.09 5326.42 1039.76 5326.33
 1065.77 5327.03 1108.88    5327 1135.28  5327.2 1153.68 5329.16 1162.17 5329.71
 1165.58 5329.76 1173.95 5329.62 1185.06 5326.77 1207.44 5326.67 1214.35 5327.75
 1226.84 5327.91 1251.08 5329.85 1268.89  5331.6  1298.4 5330.73 1377.25 5330.53
 1396.35 5330.95 1397.01 5331.13 1400.64 5333.88 1432.52 5338.07 1439.71 5338.43
 1458.07 5339.86 1472.24 5340.32  1489.6 5340.57 1505.61 5339.69  1508.6 5339.77
#Mann= 3 , 0 , 0
     970    .044       0    1000    .034       0 1226.84    .044       0
Bank Sta=1000,1226.84
Sediment Elevation=0
Exp/Cntr=0.3,0.1

Type RM Length L Ch R = 1 ,24217.  ,495,417,305
#Sta/Elev= 30
    1000 5335.72 1002.34 5334.12 1007.65 5331.76 1027.71 5324.64  1029.4 5323.82
  1032.9 5322.83 1040.53 5321.82 1064.15 5320.54 1111.39 5320.62 1136.95 5321.59
 1146.57 5323.57 1152.65    5324  1164.3 5325.74 1181.98 5326.26 1191.63 5325.76
 1204.39 5325.56 1215.41 5326.04 1231.51 5325.98 1256.71 5326.61 1291.71 5326.91
  1305.3 5326.08 1320.65 5325.51 1330.99 5325.95 1336.02  5325.7 1354.46 5325.89
 1367.49 5326.84 1379.09 5327.11 1389.55 5328.08 1396.52 5327.44  1422.3 5327.08
#Mann= 3 , 0 , 0
    1000    .044       0 1040.53    .034       0 1136.95    .044       0
#Block Obstruct= 2 , 0
                            1400
Bank Sta=1040.53,1136.95
Sediment Elevation=0
Exp/Cntr=0.3,0.1

Type RM Length L Ch R = 1 ,23800   ,390,382,370
BEGIN DESCRIPTION:
US limit of caliche
END DESCRIPTION:
#Sta/Elev= 27
    1000 5351.97 1005.61 5350.49 1008.87 5348.95 1011.18 5347.55 1018.66 5343.61
 1026.41 5339.83 1035.23 5334.58 1039.94  5332.1 1043.72 5328.15 1058.17 5317.56
 1061.55 5315.42  1075.2  5312.2 1081.15  5312.2 1103.06 5312.66 1104.05 5312.56
 1118.27 5312.88 1134.54 5314.96 1144.37 5316.08 1155.33 5317.86 1161.82  5318.8
 1167.65 5319.27 1191.27 5320.79 1199.99 5321.47 1223.92  5324.1 1233.69 5325.05
 1235.24 5325.29  1239.6 5325.34
#Mann= 3 , 0 , 0
    1000    .044       0 1061.55    .034       0 1134.54    .044       0
Bank Sta=1061.55,1134.54
Sediment Elevation=0
Exp/Cntr=0.3,0.1

Type RM Length L Ch R = 1 ,23418.  ,363,383,411
#Sta/Elev= 29
    1000 5322.72 1000.03 5322.71 1001.94 5322.03 1017.17 5317.03 1017.94 5316.91
 1040.19 5312.96 1047.83 5312.67 1054.66 5312.89 1060.98 5310.59 1078.09 5305.42
  1084.5 5304.82 1090.29 5304.74 1094.65 5304.74 1119.13 5304.44 1126.33 5304.17
 1130.32 5304.22 1133.83 5304.26 1152.48 5304.62 1155.97 5304.12 1155.99 5304.12
 1160.41 5304.48 1177.32 5307.29 1187.66 5308.96 1192.49 5309.13 1197.81 5309.55
 1218.37 5314.79 1219.89 5315.24 1220.28 5315.33 1224.96  5315.7
#Mann= 3 , 0 , 0
    1000    .044       0 1060.98    .034       0 1177.32    .044       0
Bank Sta=1060.98,1177.32
Sediment Elevation=0
Exp/Cntr=0.3,0.1